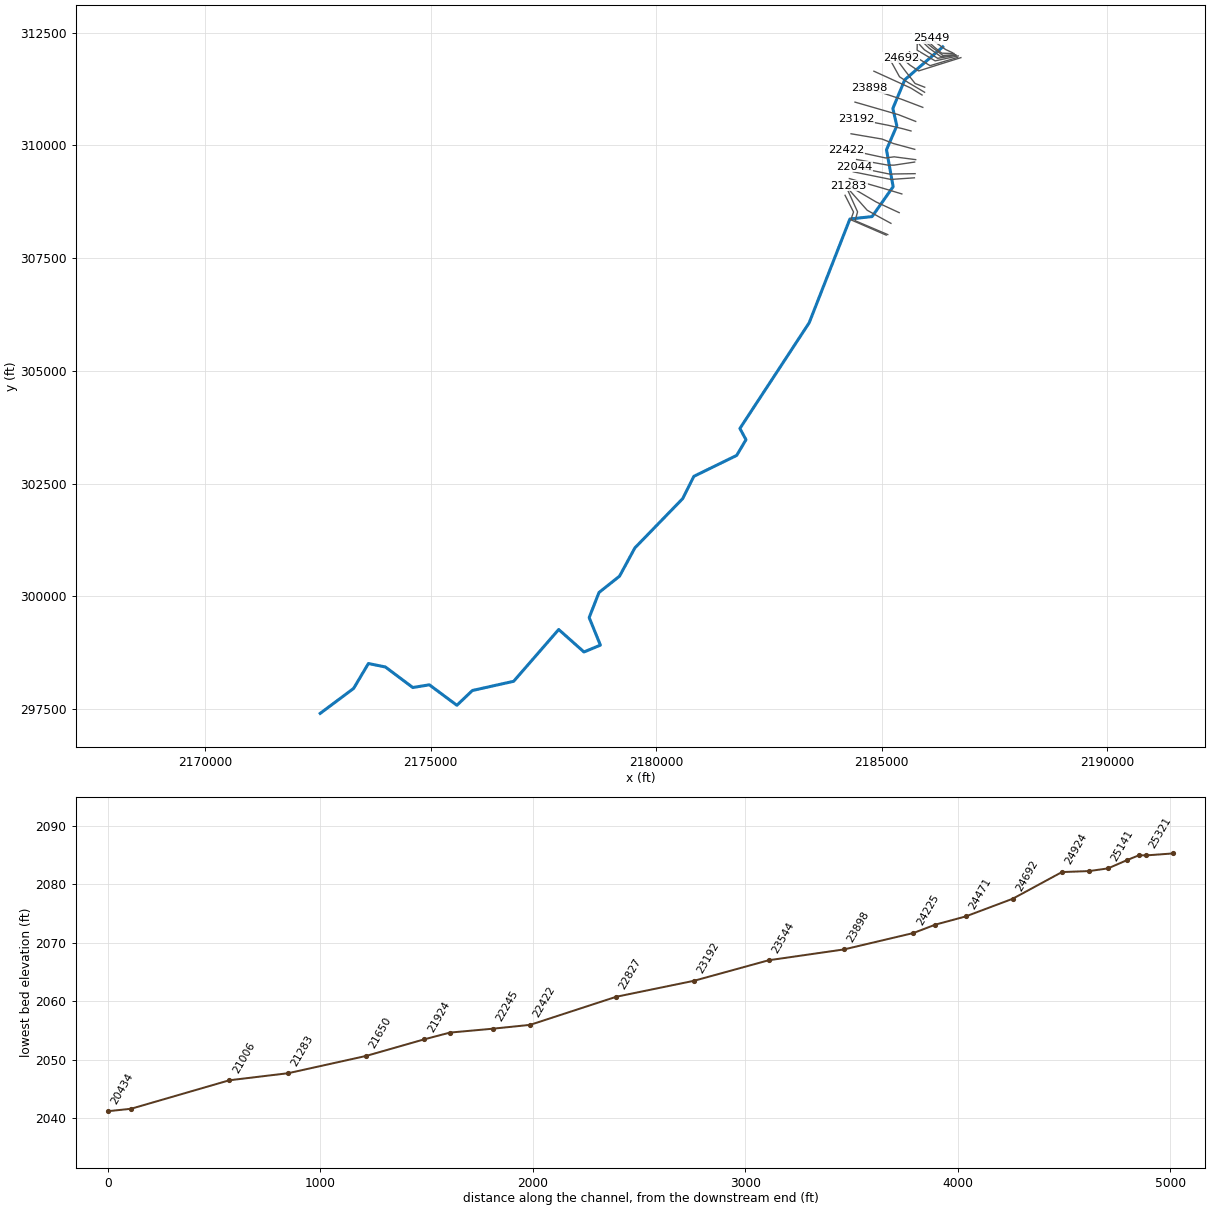
--- HOWARDCK.prj (project) ---

Proj Title=HOWARDCK
Current Plan=p01
Default Exp/Contr=0,0
English Units
Geom File=g01
Flow File=f01
Plan File=p01
BEGIN DESCRIPTION:
Stream Name- Howard Creek
Flood Zone: Zone A
Greenbrier County, WV
County-Wide Study
WVDHSEM-2018-3, Flood Risk Project
HEC-RAS Version: 5.0.7
General Notes:
For the Hydrology HECHMS 4.2.1 was used.
DS Boundary Conditions from Disaster Study of Howard Creek
END DESCRIPTION:
DSS Export Rating Curves= 0
DSS Export Rating Curve Sorted= 0
DSS Export Volume Flow Curves= 0
DXF Filename=H:\CTP\WV\f05_Greenbrier_RiskMAP\f05_HH_Modeling\f02_Hydraulics\H1\Remaining\splitted_models\HOWARDCK\GRBRRVTR1.
DXF OffsetX= 0
DXF OffsetY= 0
DXF ScaleX= 0
DXF ScaleY= 0

--- HOWARDCK.p01 (plan) ---

Plan Title=Floodplain
Program Version=5.07
Short Identifier=Floodplain
Geom File=g01
Flow File=f01
Subcritical Flow
K Sum by GR= 0
Std Step Tol= 0.01
Critical Tol= 0.01
Num of Std Step Trials= 20
Max Error Tol= 0.3
Flow Tol Ratio= 0.001
Split Flow NTrial= 30
Split Flow Tol= 0.02
Split Flow Ratio= 0.02
Log Output Level= 0
Friction Slope Method= 1
Unsteady Friction Slope Method= 2
Unsteady Bridges Friction Slope Method= 1
Parabolic Critical Depth
Global Vel Dist= 0 , 0 , 0
Global Log Level= 0
CheckData=True
Encroach Param=-1 ,0,0, 0
Mapping Interval=1HOUR
Computation Time Step Use Courant=        0
Computation Time Step Use Time Series=    0
Computation Time Step Count To Double=0
Computation Time Step Max Doubling=0
Computation Time Step Max Halving=0
Computation Time Step Residence Courant=0
Run HTab= 0
Run UNet= 0
Run Sediment= 0
Run PostProcess= 0
Run WQNet= 0
Run RASMapper= 0
UNET Theta= 0
UNET Theta Warmup= 0
UNET ZTol= 0
UNET ZSATol= 0
UNET MxIter= 0
UNET Max Iter WO Improvement= 0
UNET MaxInSteps= 0
UNET DtIC= 0
UNET DtMin= 0
UNET MaxCRTS= 0
UNET WFStab= 0
UNET SFStab= 0
UNET WFX= 1
UNET SFX= 1
UNET 1D Methodology=Finite Difference
UNET DSS MLevel= 1
UNET Pardiso=0
UNET DZMax Abort= 0
UNET Use Existing IB Tables= 0
UNET Froude Reduction=False
UNET Froude Limit= 0
UNET Froude Power= 0
UNET D1 Cores= 0
UNET D2 Coriolis=0
UNET D2 Cores= 0
UNET D2 Theta= 1
UNET D2 Theta Warmup= 1
UNET D2 Z Tol= 0.01
UNET D2 Volume Tol= 0.01
UNET D2 Max Iterations= 20
UNET D2 Equation= 0
UNET D2 RampUpFraction=0.1
UNET D2 TimeSlices= 1
UNET D2 BCVolumeCheck=0
UNET D1D2 MaxIter= 0
UNET D1D2 ZTol=0.01
UNET D1D2 QTol=0.1
UNET D1D2 MinQTol=1
Write IC File= 0
Write IC File at Fixed DateTime=0
Write IC File at Sim End=0
Echo Input=False
Echo Parameters=False
Echo Output=False
Write Detailed= 0
HDF Write Warmup=0
HDF Write Time Slices=0
HDF Flush=0
HDF Face Node Velocities=0
HDF Compression= 1
HDF Chunk Size= 1
HDF Spatial Parts= 1
HDF Use Max Rows=0
HDF Fixed Rows= 1
Calibration Method= 0
Calibration Iterations= 20
Calibration Max Change=0.05
Calibration Tolerance=0.2
Calibration Maximum=1.5
Calibration Minimum=0.5
Calibration Optimization Method= 1
WQ AD Non Conservative
WQ ULTIMATE=-1
WQ Max Comp Step=1HOUR
WQ Output Interval=15MIN
WQ Output Selected Increments= 0
WQ Output face flow=0
WQ Output face velocity=0
WQ Output face area=0
WQ Output face dispersion=0
WQ Output cell volume=0
WQ Output cell surface area=0
WQ Output cell continuity=0
WQ Output cumulative cell continuity=0
WQ Output face conc=0
WQ Output face dconc_dx=0
WQ Output face courant=0
WQ Output face peclet=0
WQ Output face adv mass=0
WQ Output face disp mass=0
WQ Output cell mass=0
WQ Output cell source sink temp=0
WQ Output nsm pathways=0
WQ Output nsm derived pathways=0
WQ Output MaxMinRange=-1
WQ Daily Max Min Mean=-1
WQ Daily Range=0
WQ Daily Time=0
WQ Create Restart=0
WQ Fixed Restart=0
WQ System Summary=0
WQ Write To DSS=0
WQ Use Fixed Temperature=0
Sorting and Armoring Iterations= 10
XS Update Threshold= 0.02
Bed Roughness Predictor= 0
Hydraulics Update Threshold= 0.02
Energy Slope Method= 1
Volume Change Method= 1
Sediment Retention Method= 0
XS Weighting Method= 0
Number of US Weighted Cross Sections= 1
Number of DS Weighted Cross Sections= 1
Upstream XS Weight=0
Main XS Weight=1
Downstream XS Weight=0
Number of DS XS's Weighted with US Boundary= 1
Upstream Boundary Weight= 1
Weight of XSs Associated with US Boundary= 0
Number of US XS's Weighted with DS Boundary= 1
Downstream Boundary Weight= 0.5
Weight of XSs Associated with DS Boundary= 0.5
Percentile Method= 0
Sediment Output Level= 3
Mass or Volume Output= 0
Output Increment Type= 1
Profile and TS Output Increment= 1
XS Output Flag= 0
XS Output Increment= 10
Write Gradation File= 0
Read Gradation Hotstart= 0
Write HDF5 File= 1
Write Binary Output= 1
Write DSS Sediment File= 0
SV Curve= 0
Specific Gage Flag= 0

--- HOWARDCK.f01 (steady flow) ---

Flow Title=Flow
Program Version=5.07
Number of Profiles= 6
Profile Names=f1p,f10p,f4p,f2p,f02p,f1pplus
River Rch & RM=HOWARDCK,Main            ,25449
    4190    2090    2840    3490    6010    4930
River Rch & RM=HOWARDCK,Main            ,16737
    4520    2250    3060    3770    6510    5330
River Rch & RM=HOWARDCK,Main            ,13262
    4810    2390    3250    4000    6930    5670
River Rch & RM=HOWARDCK,Main            ,1989
    7980    3720    5200    6515   11800    9500
Boundary for River Rch & Prof#=HOWARDCK,Main            , 1
Up Type= 0
Dn Type= 1
Dn Known WS=1885.77
Boundary for River Rch & Prof#=HOWARDCK,Main            , 2
Up Type= 0
Dn Type= 1
Dn Known WS=1884.59
Boundary for River Rch & Prof#=HOWARDCK,Main            , 3
Up Type= 0
Dn Type= 1
Dn Known WS=1885.21
Boundary for River Rch & Prof#=HOWARDCK,Main            , 4
Up Type= 0
Dn Type= 1
Dn Known WS=1885.53
Boundary for River Rch & Prof#=HOWARDCK,Main            , 5
Up Type= 0
Dn Type= 1
Dn Known WS=1886.34
Boundary for River Rch & Prof#=HOWARDCK,Main            , 6
Up Type= 0
Dn Type= 1
Dn Known WS=1886.04
DSS Import GetInterval= 0
DSS Import GetPeak= 0
DSS Import FillOption= 0

--- HOWARDCK.g01 (geometry) ---

Geom Title=Geometry
Program Version=5.07

River Reach=HOWARDCK        ,Main
Reach XY= 30
2186353.93215817312182.4589496572185511.19500001311452.457000016
2185247.03100001310816.648999994     2185334.947310431.588000012
     2185105.842309900.9439999962185253.49600001309082.200000001
2184786.57000001308419.3349999982184294.68399999308365.557999996
2183391.63400001       306063.85     2181855.432 303720.53800002
     2181990.285303471.393999997     2181783.514      303122.867
2180834.29300001302659.1500000012180586.88100001302165.080000019
2179526.30000001301072.1340000232179186.70600001300445.707000006
2178730.66000001300083.183000001     2178512.948299527.192000001
2178761.89100001298915.978000026     2178397.611298764.511000007
2177837.15000001299262.626000008     2176838.484298114.272999997
     2175923.136297909.991000009     2175579.206297582.196000014
2174968.55400001298036.435000014      2174602.15297975.816000023
     2173994.594298431.209000021     2173617.949298508.260999995
     2173289.014297955.6750000242172548.69136636297402.822373667

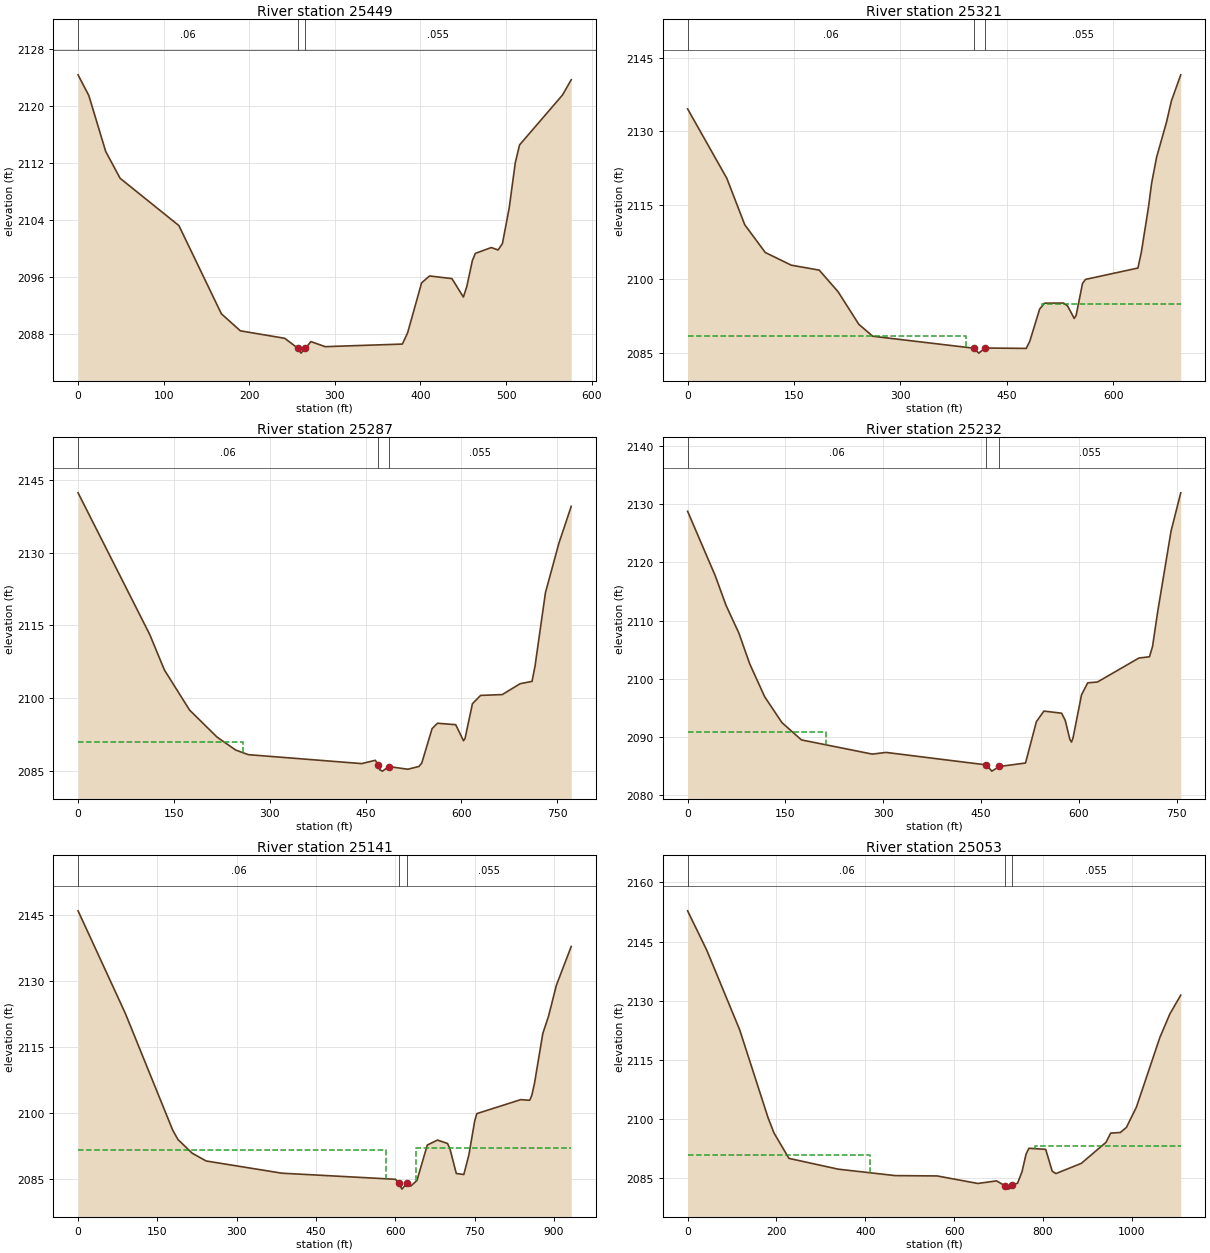
Type RM Length L Ch R = 1 ,25449   ,128.3,128.3,128.3
XS GIS Cut Line= 4
2186572.99815229 312051.612689452186415.29561911312124.999016774
2186237.29474006312251.4733255662186098.32914152312371.701989479
#Sta/Elev= 30
       0 2124.36    12.6 2121.44    32.3  2113.6    49.1 2109.84   117.8  2103.2
   167.4 2090.82   189.6 2088.43   241.4 2087.38   256.4 2086.02   260.4  2085.3
   265.5 2085.96     272 2086.92   288.6 2086.21   378.8 2086.57   384.9 2088.13
   401.3 2095.17   410.6 2096.13   436.7 2095.76   450.1 2093.17   454.1 2094.65
   460.6 2098.29   464.1  2099.3   482.7 2100.12   490.6 2099.78   495.7 2100.67
   503.6 2105.67   510.7    2112   515.7 2114.52   565.9 2121.53576.0554 2123.67
#Mann= 3 , 0 , 0
       0     .06       0   256.4    .045       0   265.5    .055       0
Bank Sta=256.4,265.5
XS Rating Curve= 0 ,0
Exp/Cntr(USF)=0,0
Exp/Cntr=0.5,0.3

Type RM Length L Ch R = 1 ,25321   ,33.6,33.6,33.6
XS GIS Cut Line= 4
 2186605.7877879312034.4371660342186332.54082446312042.244222132
2186165.46982396312178.0869982422186012.45152443312317.052596791
#Sta/Elev= 30
       0 2134.59    55.3 2120.48    80.6 2111.04   109.5 2105.41   146.2 2102.83
   185.6 2101.83   212.2 2097.43   241.4 2090.82   261.1 2088.39   403.2 2085.97
   410.6 2084.96   419.5    2086   477.5 2085.92   482.5 2087.37   496.4  2093.9
   503.2 2095.11   530.1 2095.14   535.9 2094.53   545.2 2092.01   547.8 2092.61
   556.9 2099.13   561.1 2099.94     635 2102.25   639.9 2105.53   649.8 2114.56
   654.3 2119.48   661.3 2124.76   675.3  2131.9   682.2 2136.22695.3889 2141.51
#Mann= 3 , 0 , 0
       0     .06       0   403.2    .045       0   419.5    .055       0
#XS Ineff= 2 , 0
       0     392 2088.42  499.13       0 2095.01
Permanent Ineff=
       F       F
Bank Sta=403.2,419.5
XS Rating Curve= 0 ,0
Exp/Cntr(USF)=0,0
Exp/Cntr=0.5,0.3

Type RM Length L Ch R = 1 ,25287   ,55.3,55.3,55.3
XS GIS Cut Line= 4
2186633.89318986312009.454586519 2186359.0848152311992.279063103
2186138.92583323312154.6658299472185965.60918784312295.192839716
#Sta/Elev= 30
       0 2142.29   112.2 2113.12   135.2 2105.81   174.6 2097.56   217.4 2092.02
   246.9 2089.32   266.7 2088.38     444 2086.54   465.3 2087.22     470 2086.31
   472.5 2085.25   476.6 2084.99   486.4 2085.93   516.4 2085.38   533.7 2085.96
   538.1 2086.66   554.2 2093.73   562.7 2094.85   591.2 2094.55   603.4 2091.25
   605.8 2091.71   617.4 2098.87   630.2 2100.58   664.1 2100.75   692.1 2102.99
   710.7 2103.47   715.4 2106.62   731.7 2121.73   752.7 2131.89772.0414  2139.5
#Mann= 3 , 0 , 0
       0     .06       0     470    .045       0   486.4    .055       0
#XS Ineff= 2 , 0
          258.39 2091.05  572.42          2094.6
Permanent Ineff=
       F       F
Bank Sta=470,486.4
XS Rating Curve= 0 ,0
Exp/Cntr(USF)=0,0
Exp/Cntr=0.5,0.3

Type RM Length L Ch R = 1 ,25232   ,90.7,90.7,90.7
XS GIS Cut Line= 4
2186583.92803083311993.8404743232186307.55824495311968.857894808
2186056.17103858312149.9815962882185934.38096345312267.087437762
#Sta/Elev= 30
       0 2128.75    42.5 2117.66    58.9 2112.62    78.7 2107.83    95.2 2102.59
   118.2 2096.93   144.6  2092.5   174.5 2089.53   283.2 2087.09   304.3 2087.38
   458.1 2085.24   466.5 2084.17   478.3 2084.97   518.2 2085.56   534.9 2092.66
   546.4 2094.47   573.6 2094.11   579.2 2092.85   586.3 2089.59   588.7 2089.16
     591 2089.82   604.1 2097.26   613.6 2099.32   628.5 2099.46   692.2 2103.58
   708.3 2103.79     713 2105.55   720.9 2111.51   741.4 2125.35756.2949 2131.92
#Mann= 3 , 0 , 0
       0     .06       0   458.1    .045       0   478.3    .055       0
#XS Ineff= 2 , 0
          212.67 2090.88  550.56         2094.27
Permanent Ineff=
       F       F
Bank Sta=458.1,478.3
XS Rating Curve= 0 ,0
Exp/Cntr(USF)=0,0
Exp/Cntr=0.5,0.3

Type RM Length L Ch R = 1 ,25141   ,88.2,88.2,88.2
XS GIS Cut Line= 4
2186652.63012449311996.963296762 2186240.4175625311928.261203097
2185946.87225321312117.1919606762185834.45064539312238.982035809
#Sta/Elev= 30
       0 2145.91    89.3 2122.66   179.1  2096.1     189 2093.99   215.7 2090.91
   242.3 2089.13   385.3 2086.36   600.5 2084.97   606.2 2084.06   612.7 2082.74
   621.5 2084.04   629.3 2083.44     641 2084.71   660.5 2092.74   679.8 2093.87
   698.8 2093.11   703.5 2091.83   715.4 2086.29   729.6 2086.06   739.1 2090.46
   750.3 2098.27   754.2 2099.88   837.2 2103.05   854.2 2102.91   858.1 2103.96
   863.2  2106.7     879 2118.06     890 2122.06   904.6 2128.99932.7334 2137.82
#Mann= 3 , 0 , 0
       0     .06       0   606.2    .045       0   621.5    .055       0
#XS Ineff= 2 , 0
       0  582.61 2091.73  639.75       0 2092.01
Permanent Ineff=
       F       F
Bank Sta=606.2,621.5
XS Rating Curve= 0 ,0
Exp/Cntr(USF)=0,0
Exp/Cntr=0.5,0.3

Type RM Length L Ch R = 1 ,25053   ,119.9,128.6,127.5
XS GIS Cut Line= 4
2186695.63885893311982.2166544932186185.19578053311871.915704366
2185785.04964094312109.6991450122185787.65132442312231.978268571
#Sta/Elev= 30
       02152.811  43.444 2142.75 117.2892122.633 181.0632100.381  194.492096.498
 228.0552090.077 338.8212087.345 467.184 2085.71 561.7622085.625 653.3552083.715
 695.3352084.375 714.4172083.129 723.2492082.283 729.6832083.407 742.5162083.758
 752.581 2086.66 761.7832091.149 768.2052092.634  806.012092.362 820.6452086.833
 828.9092086.219 886.1552088.816 941.6072094.127 952.3072096.484 973.9322096.633
  987.69 2097.931010.0852103.0341062.9742120.7171085.5612126.7031109.9972131.437
#Mann= 3 , 0 , 0
       0     .06       0 714.417    .045       0 729.683    .055       0
#XS Ineff= 2 , 0
          409.94 2090.92  782.82         2093.32
Permanent Ineff=
       F       F
Bank Sta=714.417,729.683
XS Rating Curve= 0 ,0
Exp/Cntr(USF)=0,0
Exp/Cntr=0.5,0.3

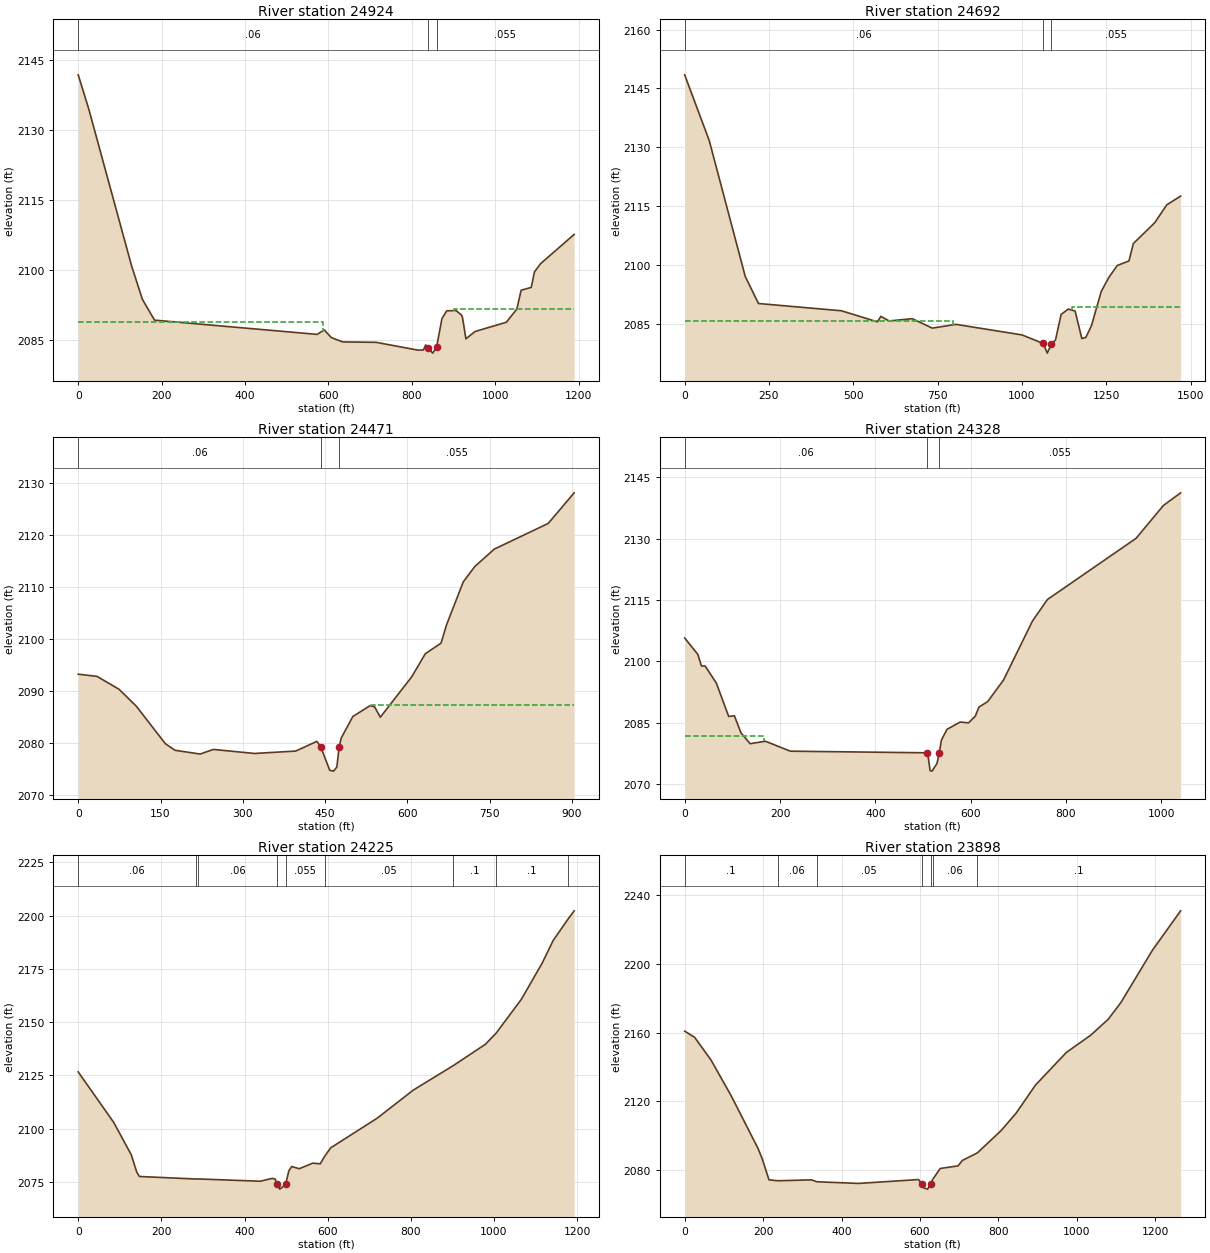
Type RM Length L Ch R = 1 ,24924   ,232.6,231.6,230.4
XS GIS Cut Line= 4
2186683.85834889311948.5595489532186071.78515078311765.874436253
2185759.50290685311953.2437826122185615.85307464312071.911035306
#Sta/Elev= 30
       0 2141.92    25.2 2134.61   128.3 2100.77     154 2093.66     183  2089.2
     573 2086.14   590.1 2087.09   607.2 2085.43   634.6 2084.52   714.5 2084.43
   814.3 2082.76   827.7 2082.77   833.4 2083.88   838.12083.225   850.2 2082.11
   859.5 2083.44   872.3 2089.54   883.7 2091.19   905.8 2091.27   919.5 2090.27
   921.9 2089.61   929.7 2085.18   951.7 2086.76  1026.8 2088.75  1051.9  2091.6
  1062.2 2095.63  1086.4 2096.24  1094.1 2099.55  1108.6 2101.32  1189.3 2107.62
#Mann= 3 , 0 , 0
       0     .06       0   838.1    .045       0   859.5    .055       0
#XS Ineff= 2 , 0
          587.33 2088.87  901.86          2091.6
Permanent Ineff=
       F       F
Bank Sta=838.1,859.5
XS Rating Curve= 0 ,0
Exp/Cntr(USF)=0,0
Exp/Cntr=0.3,0.1

Type RM Length L Ch R = 1 ,24692   ,225.2,221.1,205.6
XS GIS Cut Line= 4
2186755.47757896311943.1914022942185818.87152618311649.201169057
2185631.55031562311774.0819760962185431.22068766311945.793085774
#Sta/Elev= 30
       0 2148.46    72.8 2131.72   179.6 2097.09   218.8 2090.19   464.9 2088.34
   571.4 2085.52   581.8 2086.92   606.2 2085.75   674.6 2086.33   734.4 2083.92
   804.4 2084.88  1000.3 2082.19  1063.3 2080.01  1075.1 2077.55    1087 2079.77
  1099.7 2080.94  1116.3 2087.41  1137.5 2088.78  1157.9 2088.26  1177.6 2081.27
  1189.5 2081.55  1206.2 2084.53  1235.3 2093.28  1257.8 2096.84  1282.9 2099.88
  1317.5 2101.04  1330.4 2105.46  1393.9 2110.78  1429.5 2115.331470.644 2117.56
#Mann= 3 , 0 , 0
       0     .06       0  1063.3    .045       0    1087    .055       0
#XS Ineff= 2 , 0
          797.02 2085.75 1148.82         2089.18
Permanent Ineff=
       F       F
Bank Sta=1063.3,1087
XS Rating Curve= 0 ,0
Exp/Cntr(USF)=0,0
Exp/Cntr=0.3,0.1

Type RM Length L Ch R = 1 ,24471   ,136.9,143.4,146.6
XS GIS Cut Line= 4
2185953.69730407311287.6084190482185739.72744648311370.818919221
2185528.72939247311639.7671429932185331.10445456311907.229464977
#Sta/Elev= 30
       0  2093.2    34.2 2092.78    74.4  2090.3   106.1 2087.01   158.9 2079.81
   176.5 2078.54   222.3 2077.82   246.3 2078.71   321.3 2077.93   396.4 2078.39
     435 2080.26     442 2079.23   458.4 2074.71   465.4 2074.53   471.4  2075.3
   475.6 2079.17   479.4  2080.9   500.6 2085.05   532.1 2087.14   540.2 2086.92
   550.7 2084.92   608.1 2092.72   632.7 2097.14   661.3 2099.17   671.4 2102.71
   701.9 2110.98     723 2113.94   758.2 2117.27   856.8 2122.23903.9717 2128.12
#Mann= 3 , 0 , 0
       0     .06       0     442    .045       0   475.6    .055       0
#XS Ineff= 2 , 0
                          532.93         2087.26
Permanent Ineff=
       F       F
Bank Sta=442,475.6
XS Rating Curve= 0 ,0
Exp/Cntr(USF)=0,0
Exp/Cntr=0.5,0.3

Type RM Length L Ch R = 1 ,24328   ,101.1,103,105.4
XS GIS Cut Line= 4
2185950.72550049311176.1657848882185589.65136581311390.135642475
2185394.99823148311519.4090981012185207.77460609311858.194705946
#Sta/Elev= 30
       0 2105.69    27.6 2101.68    35.2 2098.84    42.9 2098.84    66.5 2094.64
    92.4 2086.49   104.3 2086.67     118 2082.51   137.3 2079.83   169.4 2080.43
   221.7    2078     508  2077.6     511 2076.52   514.9 2073.25   518.9 2073.12
   529.3 2074.99     534  2077.5   538.6  2080.7   550.4 2083.35     578 2085.12
   595.5 2084.93   609.7 2086.56   617.3 2088.78   635.8 2090.14     669 2095.42
   729.6 2109.83     761  2115.1   946.9 2130.06  1004.6 2138.131040.458  2141.2
#Mann= 3 , 0 , 0
       0     .06       0     508    .045       0     534    .055       0
#XS Ineff= 2 , 0
          167.06 2081.66
Permanent Ineff=
       F       F
Bank Sta=508,534
XS Rating Curve= 0 ,0
Exp/Cntr(USF)=0,0
Exp/Cntr=0.5,0.3

Type RM Length L Ch R = 1 ,24225   ,324.4,326.4,326.9
XS GIS Cut Line= 4
2185894.70869635311115.3518222892185645.40938005311269.086400678
2185246.53047396311451.9058993032184826.87662484311643.035375137
#Sta/Elev= 30
       0 2126.66    85.4 2102.98   127.8 2087.73   140.7 2079.72   147.1 2077.62
  283.362076.432  289.252076.462   437.9 2075.39   466.6 2076.74     474  2076.4
  477.432073.872   484.8 2071.69  498.842073.877   506.5 2080.22   513.6  2082.3
   531.7 2081.26   564.2 2083.89   582.2 2083.57  592.852087.144   607.5 2091.09
   719.4    2105   805.9 2118.14  901.842129.588   979.1  2139.6  1004.8 2144.75
  1065.5 2160.62    1116 2177.74  1142.5 2188.37 1178.312198.404  1192.8 2202.22
#Mann= 9 ,-1 , 0
       0     .06       0  283.36     .05       0  289.25     .06       0
  477.43    .045       0  498.84    .055       0  592.85     .05       0
  901.84      .1       0  1004.8      .1       0 1178.31      .1       0
Bank Sta=477.43,498.84
XS Rating Curve= 0 ,0
Exp/Cntr(USF)=0,0
Exp/Cntr=0.5,0.3

Type RM Length L Ch R = 1 ,23898   ,352.6,354.3,354.3
XS GIS Cut Line= 3
2185911.32865078310841.122574352 2185441.8149384311019.787084372
2184718.84692111311260.776423468
#Sta/Elev= 30
       0 2160.95    25.4 2157.34    67.5    2144   118.7 2123.22   186.8 2092.69
   197.4 2086.75   214.9 2074.33  237.442073.751   323.8 2074.29  336.552073.193
   443.1 2072.21   596.1 2074.47  604.872071.885     610  2069.6   619.4 2068.89
  628.112071.881  632.18 2074.52   651.5 2080.92   697.2 2082.46   707.6 2085.54
   746.4 2090.05   807.1 2103.08   845.4 2113.27   894.3 2129.49   973.1 2148.54
  1035.4 2158.61  1080.3 2167.99  1112.2 2177.65  1192.9 2208.22  1264.4 2231.05
#Mann= 7 ,-1 , 0
       0      .1       0  237.44     .06       0  336.55     .05       0
  604.87    .045       0  628.11     .05       0  632.18     .06       0
   746.4      .1       0
Bank Sta=604.87,628.11
XS Rating Curve= 0 ,0
Exp/Cntr(USF)=0,0
Exp/Cntr=0.3,0.1

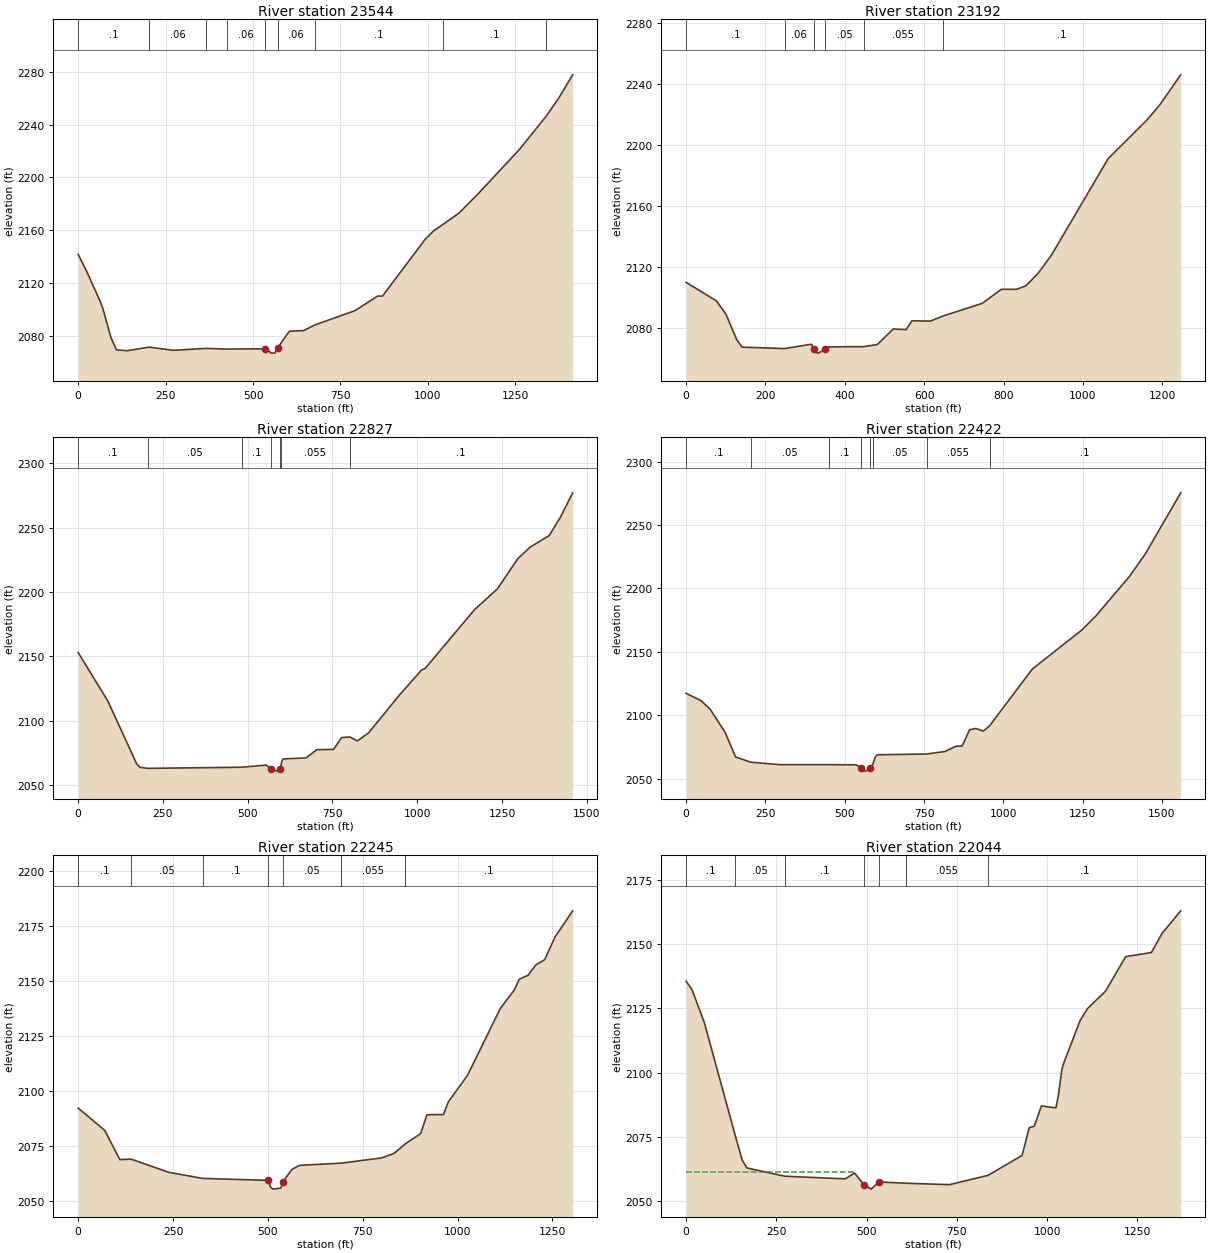
Type RM Length L Ch R = 1 ,23544   ,342.1,351.6,347.5
XS GIS Cut Line= 3
2185753.43908378 310529.498428972185371.18013211310679.078018753
2184407.22277573310957.462255295
#Sta/Elev= 30
       0 2141.76    24.2 2129.06    63.8 2105.68    70.8 2100.65    93.9 2078.73
   109.6 2069.46   140.6  2068.9  202.942071.569   271.6 2069.16  364.422070.618
  424.23 2070.12   535.4 2070.32   552.5 2067.04   562.8 2067.16   570.6 2071.07
   603.7 2083.61   644.7 2084.09  675.942088.276   791.6  2099.2   856.4 2110.23
   870.1  2110.2     993 2153.43  1016.9 2159.66 1044.232164.644  1088.7 2172.96
  1143.3 2187.54  1262.8 2221.48 1338.642246.503  1373.5 2259.75  1413.8 2277.59
#Mann= 9 ,-1 , 0
       0      .1       0  202.94     .06       0  364.42     .05       0
  424.23     .06       0   535.4    .045       0   570.6     .06       0
  675.94      .1       0 1044.23      .1       0 1338.64      .1       0
Bank Sta=535.4,570.6
XS Rating Curve= 0 ,0
Exp/Cntr(USF)=0,0
Exp/Cntr=0.3,0.1

Type RM Length L Ch R = 1 ,23192   ,366.6,365.8,362.3
XS GIS Cut Line= 4
2185649.56436865310317.5940101092185466.74487003310367.453873371
2185150.96573604310442.2436682632184432.15270736310583.513280836
#Sta/Elev= 30
       0 2109.84    76.1 2097.76   100.2 2089.11   127.3 2072.49   140.9 2067.45
  248.212066.513   313.6 2069.28   316.7 2069.19  321.242066.095   323.4 2064.33
   333.5 2063.53  350.392066.096   360.5 2067.64  447.372067.785   481.9 2069.16
   522.3 2079.37   554.5  2078.9   569.1  2084.7     616  2084.5  646.282087.707
   746.3 2096.13   794.8 2105.33   833.2 2105.33   856.6 2107.63   886.7 2115.64
   920.6 2127.61  1063.9 2190.92  1160.9 2216.02  1194.2 2226.16  1246.6 2245.77
#Mann= 6 ,-1 , 0
       0      .1       0  248.21     .06       0  321.24    .045       0
  350.39     .05       0  447.37    .055       0  646.28      .1       0
Bank Sta=321.24,350.39
XS Rating Curve= 0 ,0
Exp/Cntr(USF)=0,0
Exp/Cntr=0.3,0.1

Type RM Length L Ch R = 1 ,22827   ,392.7,405,406.9
XS GIS Cut Line= 4
2185732.66414076309910.4051268092185258.99543977310039.209773568
2185005.54113486 310138.929500092184319.96801502310255.269181033
#Sta/Elev= 30
       0 2153.01      88 2115.09   172.6 2066.44   182.8 2063.72  205.362062.957
  482.862063.825   554.8  2065.5  569.962062.423   587.5  2060.8  595.292062.428
  598.032065.177   601.6 2069.32   605.1 2070.33   672.1 2071.06   703.8 2077.48
   753.2 2077.69     777 2086.82  800.452087.435   823.6 2084.29   856.9 2090.58
   946.7 2119.67  1013.3  2139.5  1023.3 2140.59  1169.7 2186.49  1236.3 2202.35
  1296.2 2225.78  1332.8 2234.89  1389.3 2243.91  1422.6 2258.23  1458.6 2277.15
#Mann= 7 ,-1 , 0
       0      .1       0  205.36     .05       0  482.86      .1       0
  569.96    .045       0  595.29      .1       0  598.03    .055       0
  800.45      .1       0
Bank Sta=569.96,595.29
XS Rating Curve= 0 ,0
Exp/Cntr(USF)=0,0
Exp/Cntr=0.3,0.1

Type RM Length L Ch R = 1 ,22422   ,178.1,176.8,173
XS GIS Cut Line= 4
2185753.43908378309681.8807535292185275.61539419309744.205582605
2185084.48591836309719.275650975 2184220.2482885309906.250138204
#Sta/Elev= 30
       0 2117.35    46.5 2111.63    75.8 2104.73   122.6 2086.67   155.8 2067.11
  204.25 2063.03   294.8  2061.1  450.962061.115   536.1 2060.97  550.642058.312
   556.2  2056.2   565.8    2056  580.682058.313  588.612061.513   595.9 2066.88
   602.5  2068.9  757.762069.489   816.3 2071.48   850.1  2075.6     870 2075.79
   893.5 2088.55   913.4 2089.62   937.1 2087.56  956.682091.802  1091.5 2136.53
  1247.5 2167.33  1291.7 2178.39    1397 2209.38  1447.4 2227.22  1558.9 2275.42
#Mann= 8 ,-1 , 0
       0      .1       0  204.25     .05       0  450.96      .1       0
  550.64    .045       0  580.68      .1       0  588.61     .05       0
  757.76    .055       0  956.68      .1       0
Bank Sta=550.64,580.68
XS Rating Curve= 0 ,0
Exp/Cntr(USF)=0,0
Exp/Cntr=0.3,0.1

Type RM Length L Ch R = 1 ,22245   ,199.2,200.7,201.3
XS GIS Cut Line= 4
2185730.45911448309628.3937809462185271.55863161309559.822444426
2185137.93243737309559.8224444262184443.42787517309684.657441681
#Sta/Elev= 30
       0 2092.17      70 2082.04   109.8 2068.75   139.7 2068.96   239.6 2062.94
   328.3 2060.21   501.42059.305   507.4 2056.16   513.9 2055.34   533.7 2055.79
   540.2 2058.75   563.2 2064.26   582.8 2066.13   693.1 2067.13   799.6 2069.51
   832.6 2071.57   862.6 2075.95   902.6 2080.53   919.3 2089.12   962.6 2089.22
     976 2095.09    1026 2106.95  1112.6 2137.38  1149.3 2145.74  1162.6 2150.62
    1186 2152.51    1206 2157.13  1229.6 2159.56  1257.3    2170  1303.3 2181.72
#Mann= 7 ,-1 , 0
       0      .1       0   139.7     .05       0   328.3      .1       0
   501.4    .045       0   540.2     .05       0   693.1    .055       0
   862.6      .1       0
Bank Sta=501.4,540.2
XS Rating Curve= 0 ,0
Exp/Cntr(USF)=0,0
Exp/Cntr=0.3,0.1

Type RM Length L Ch R = 1 ,22044   ,118.5,120.3,119
XS GIS Cut Line= 4
2185740.76786793309370.9499105392185272.65011692309363.910545862
 2185188.1777408309358.631022354 2184387.4500088309522.296251091
#Sta/Elev= 30
       0 2135.52      16 2132.28      50 2119.59   134.7 2076.21     155 2066.05
   168.1 2062.92   273.1  2059.7   440.5 2058.67   466.7 2060.91     493 2056.37
   512.7 2054.68   533.92057.463   609.1 2056.97   729.7 2056.42   836.8 2060.06
   930.6 2067.77   950.5 2078.53   964.7 2079.18   984.1 2087.03  1024.3 2086.27
    1031 2090.85  1041.1 2101.34  1047.3 2104.11  1091.3 2120.17    1112 2124.87
  1162.1 2131.67  1217.7 2145.08  1288.9 2146.67    1319 2154.19  1370.1 2162.88
#Mann= 7 ,-1 , 0
       0      .1       0   134.7     .05       0   273.1      .1       0
     493    .045       0   533.9     .05       0   609.1    .055       0
   836.8      .1       0
#XS Ineff= 2 , 0
          461.47 2061.38
Permanent Ineff=
       F       F
Bank Sta=493,533.9
XS Rating Curve= 0 ,0
Exp/Cntr(USF)=0,0
Exp/Cntr=0.3,0.1

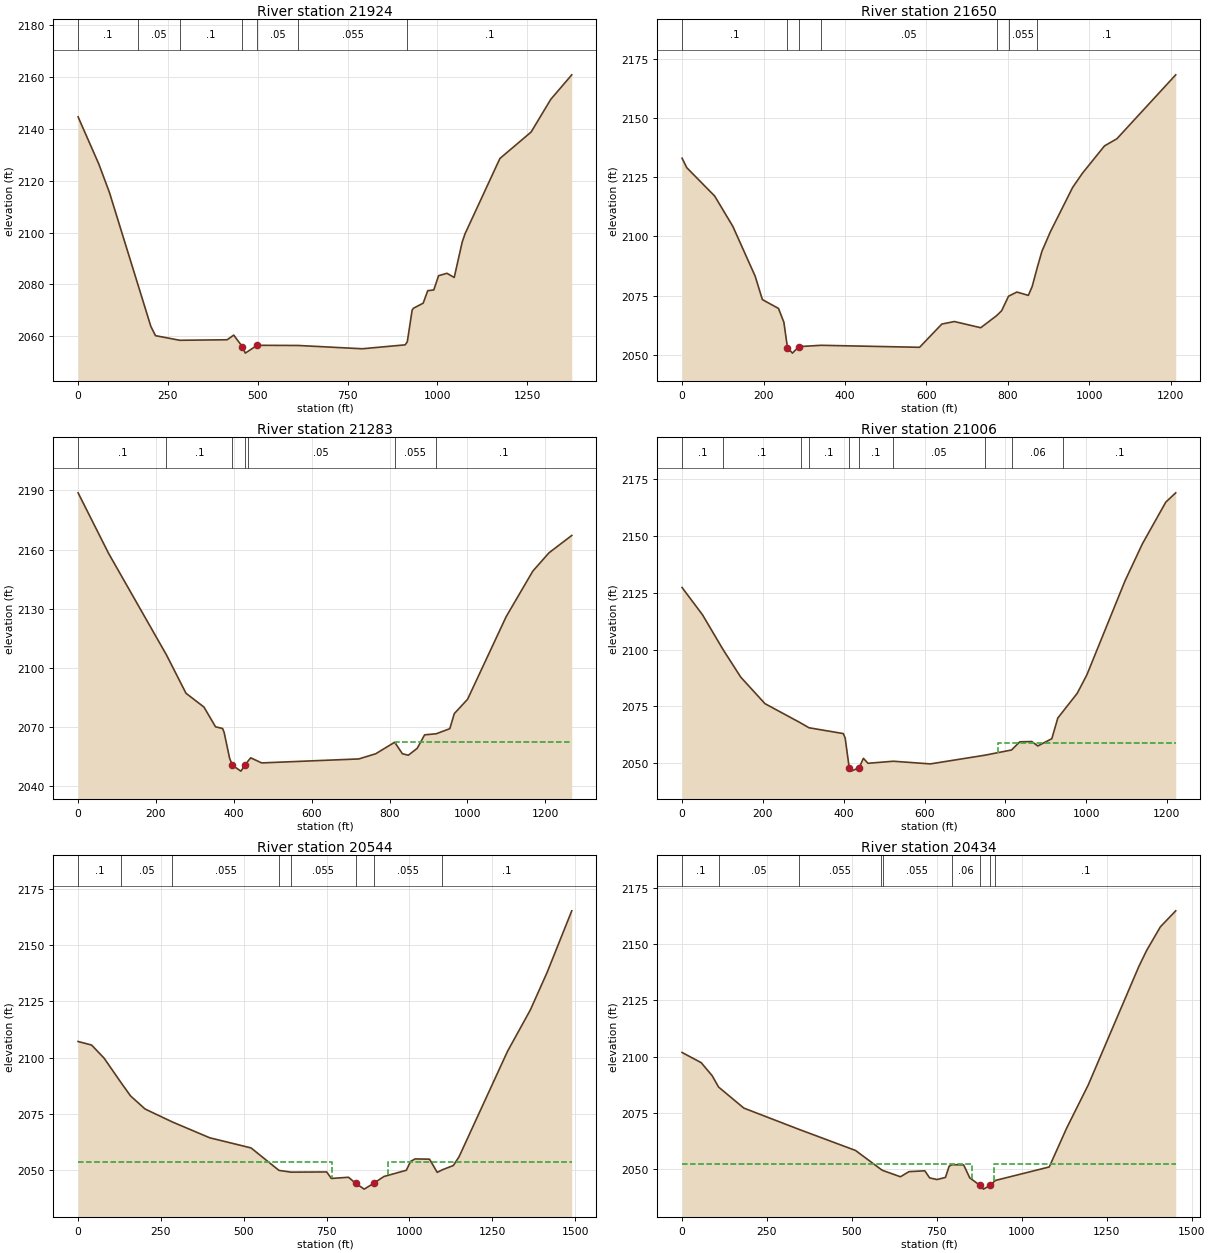
Type RM Length L Ch R = 1 ,21924   ,276.4,273.8,261.6
XS GIS Cut Line= 4
2185725.22684036309278.6347073112185297.38858686309249.330717345
2185209.47661696309241.516320021 2184369.4289046309411.479461823
#Sta/Elev= 30
       0 2144.56    57.6 2126.43    87.2 2115.46   166.1 2080.14   202.5 2063.84
   215.4 2060.26   283.1 2058.48   414.9 2058.68   433.3 2060.47   457.5 2055.96
   465.4 2053.53   498.3 2056.55   612.6 2056.48   791.1 2055.21   910.5 2056.72
   916.4 2057.89   929.8 2070.05   933.2  2070.8   960.6 2072.78   973.3 2077.59
   990.1 2077.87  1003.5 2083.37  1026.9 2084.29    1047 2082.69  1069.2 2096.32
  1077.1 2099.51  1174.2 2128.54  1261.1 2138.73  1315.6 2151.29  1374.2 2160.77
#Mann= 7 ,-1 , 0
       0      .1       0   166.1     .05       0   283.1      .1       0
   457.5    .045       0   498.3     .05       0   612.6    .055       0
   916.4      .1       0
Bank Sta=457.5,498.3
XS Rating Curve= 0 ,0
Exp/Cntr(USF)=0,0
Exp/Cntr=0.3,0.1

Type RM Length L Ch R = 1 ,21650   ,367.3,366.6,363.6
XS GIS Cut Line= 3
  2185445.969927308921.5178387952185018.00610068309050.322485553
2184282.57311758309262.226904413
#Sta/Elev= 30
       0 2133.04    11.6 2129.05    80.1 2117.06   124.7 2104.26   179.5 2083.22
   197.3  2073.3   236.8 2069.58     250 2063.76  258.922052.995   271.1 2050.69
   286.9 2053.43  341.322054.001   583.3 2053.15   637.9 2062.97   668.7 2064.04
   733.5 2061.42  772.442066.522   784.7 2068.57  801.712074.731   822.3  2076.5
   850.4 2075.09   859.9 2078.89  872.492086.986   883.8 2093.73   904.2 2101.86
   959.1 2120.68   982.8 2126.61  1037.4 2138.25  1067.8 2141.26  1212.3 2168.28
#Mann= 7 ,-1 , 0
       0      .1       0  258.92    .045       0   286.9      .1       0
  341.32     .05       0  772.44     .06       0  801.71    .055       0
  872.49      .1       0
Bank Sta=258.92,286.9
XS Rating Curve= 0 ,0
Exp/Cntr(USF)=0,0
Exp/Cntr=0.3,0.1

Type RM Length L Ch R = 1 ,21283   ,278.9,277.1,275
XS GIS Cut Line= 3
2185387.80008653308506.018978285 2184876.7364881308742.853328776
2184269.22821322309100.376474037
#Sta/Elev= 30
       0 2188.74    78.3 2158.08  226.982106.629   277.2 2087.19   323.3 2080.21
   353.1 2070.19   371.2 2069.34   375.2 2067.34   389.3  2054.2  396.642050.649
   418.2 2047.74  428.93 2050.65  435.892052.674   443.5 2054.48   471.6  2051.9
   721.2 2053.92   764.6 2056.54  813.272062.373   833.1 2056.56   848.3 2055.79
   871.2  2059.3   890.2 2066.13  919.862066.661   954.9 2069.25   966.4 2076.87
  1000.6 2084.16  1099.8 2126.05  1168.1 2149.06  1209.7 2158.35  1268.2 2167.14
#Mann= 7 ,-1 , 0
       0      .1       0  226.98      .1       0  396.64    .045       0
  428.93      .1       0  435.89     .05       0  813.27    .055       0
  919.86      .1       0
#XS Ineff= 2 , 0
                          816.86         2062.31
Permanent Ineff=
       F       F
Bank Sta=396.64,428.93
XS Rating Curve= 0 ,0
Exp/Cntr(USF)=0,0
Exp/Cntr=0.3,0.1

Type RM Length L Ch R = 1 ,21006   ,482.6,462.6,433.9
XS GIS Cut Line= 4
2185204.98058791308269.1846277942184922.44136276308422.919206183
2184677.29703506308560.0338301512184267.19264287309023.881940712
#Sta/Elev= 30
       0 2127.35    50.7 2115.32  101.622099.997   145.4 2087.87   205.2 2076.23
  293.312067.761  314.142065.618   399.1 2063.05   403.7 2061.08   413.72048.022
   418.7 2046.53  438.222048.021   448.8 2052.17     460 2049.98  522.822050.885
   614.5 2049.71  749.642053.545  815.422055.837   835.8 2059.43   865.5 2059.55
   880.4 2057.61   915.1 2060.81   929.9  2069.9  943.782073.055     978 2080.79
  1001.9 2088.94  1096.2 2130.25    1139  2146.5  1197.1 2164.92  1221.7 2169.02
#Mann= 10 ,-1 , 0
       0      .1       0  101.62      .1       0  293.31      .1       0
  314.14      .1       0   413.7    .045       0  438.22      .1       0
  522.82     .05       0  749.64    .055       0  815.42     .06       0
  943.78      .1       0
#XS Ineff= 2 , 0
                           782.5         2058.86
Permanent Ineff=
       F       F
Bank Sta=413.7,438.22
XS Rating Curve= 0 ,0
Exp/Cntr(USF)=0,0
Exp/Cntr=0.5,0.3

Type RM Length L Ch R = 1 ,20544   ,103.1,110,111
XS GIS Cut Line= 4
2185134.34578162308019.8853114882184409.71456394308327.859977142
2184464.76725187308523.4418947792184258.77576166308978.154203155
#Sta/Elev= 30
       0 2107.14    40.7 2105.57    78.6 2099.73  129.492088.913   158.3    2083
   202.1  2077.2  284.622071.443     397 2064.44   521.9 2059.94  606.142049.975
  642.552049.188   750.1 2049.28   764.3  2046.4     816 2046.92  838.132044.191
   863.4 2041.66   891.52044.192   922.9 2047.26   990.5 2050.03  1003.4 2053.95
  1016.9 2055.06  1060.4 2054.95  1083.8  2049.1 1099.232050.247  1132.3 2052.13
  1149.7 2056.04  1295.9  2102.8  1364.7 2121.13  1415.7 2137.91  1489.7  2165.1
#Mann= 8 ,-1 , 0
       0      .1       0  129.49     .05       0  284.62    .055       0
  606.14    .035       0  642.55    .055       0  838.13    .045       0
   891.5    .055       0 1099.23      .1       0
#XS Ineff= 2 , 0
          765.34  2053.6  935.88          2053.6
Permanent Ineff=
       F       F
Bank Sta=838.13,891.5
XS Rating Curve= 0 ,0
Exp/Cntr(USF)=0,0
Exp/Cntr=0.5,0.3

Type RM Length L Ch R = 1 ,20434   ,205.5,224.8,252.7
XS GIS Cut Line= 4
2185099.38970761308007.9715288252184314.77645707308348.750388215
2184375.20575421308520.5414475762184187.27837804308891.190161617
#Sta/Elev= 30
       0 2101.91    56.3 2097.39    88.5 2091.63  107.522086.559   181.8 2077.22
  343.962067.788   510.6 2058.41  586.822049.875  591.18 2049.51   642.9 2046.73
     668 2049.01   714.5 2049.38   728.8 2046.23   750.3  2045.5   775.3 2046.43
     786 2051.34  793.562052.072   828.9    2052   846.8 2046.27  876.142042.992
   887.2 2041.24  907.382042.992  922.452045.103  1080.8 2051.08  1132.2 2068.36
  1195.7 2087.52  1344.6 2140.11  1367.7 2147.25    1408 2157.71  1453.1  2164.8
#Mann= 9 ,-1 , 0
       0      .1       0  107.52     .05       0  343.96    .055       0
  586.82    .035       0  591.18    .055       0  793.56     .06       0
  876.14    .045       0  907.38     .06       0  922.45      .1       0
#XS Ineff= 2 , 0
          852.69  2052.2  919.24          2052.2
Permanent Ineff=
       F       F
Bank Sta=876.14,907.38
XS Rating Curve= 0 ,0
Exp/Cntr(USF)=0,0
Exp/Cntr=0.5,0.3