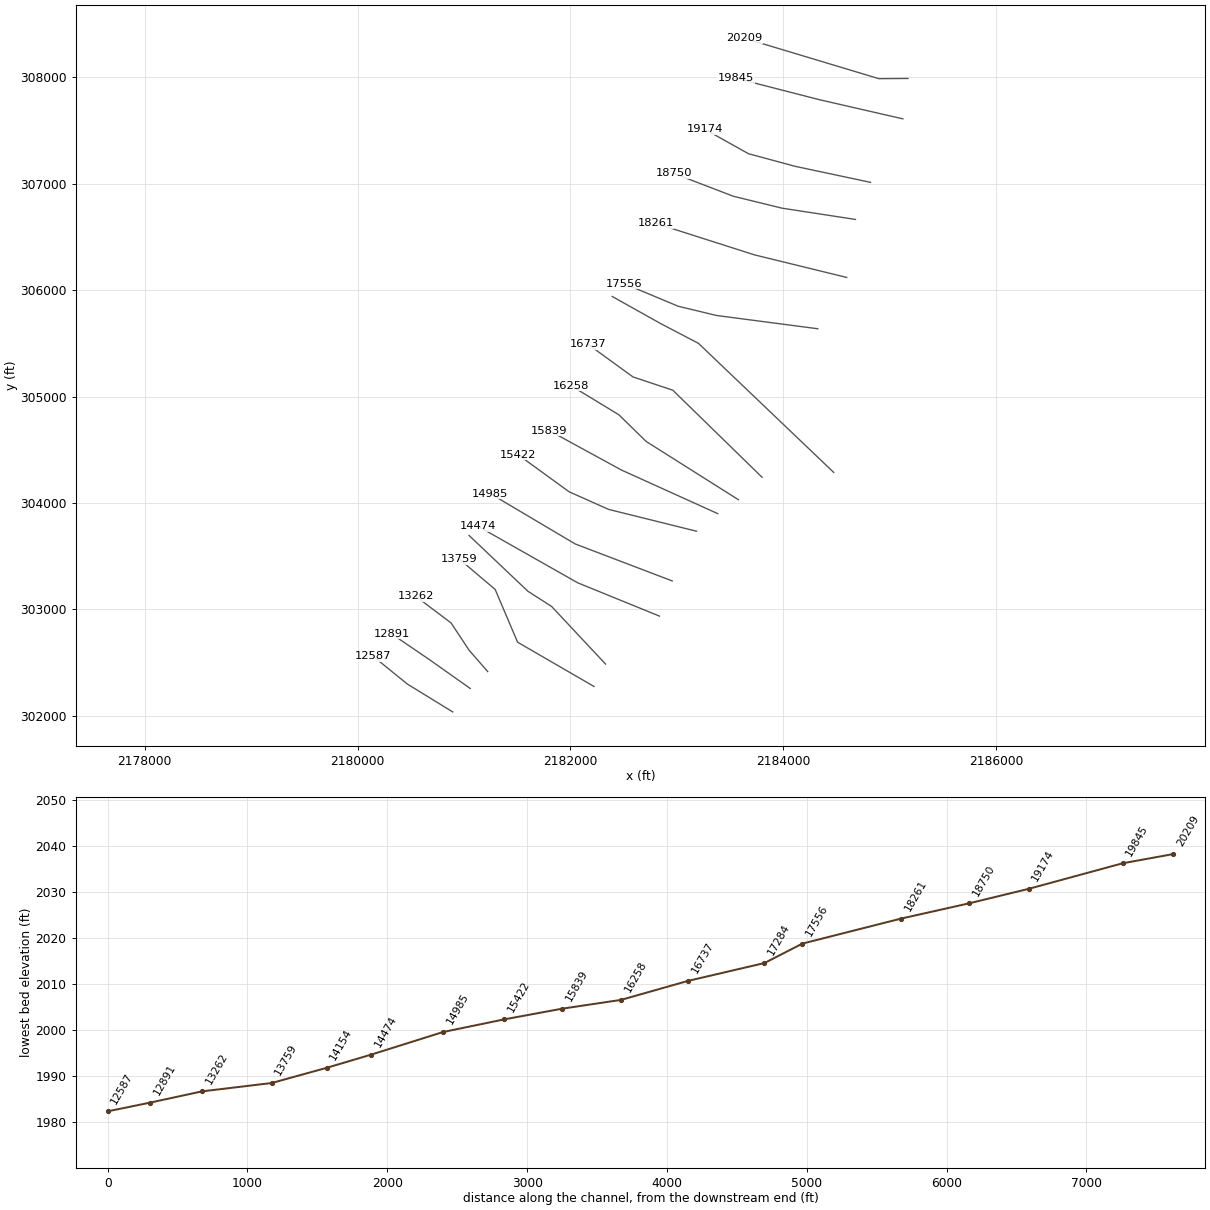
HEC-RAS study HOWARDCK.prj: HOWARDCK

--- HOWARDCK.g01 (geometry) --- (continued)

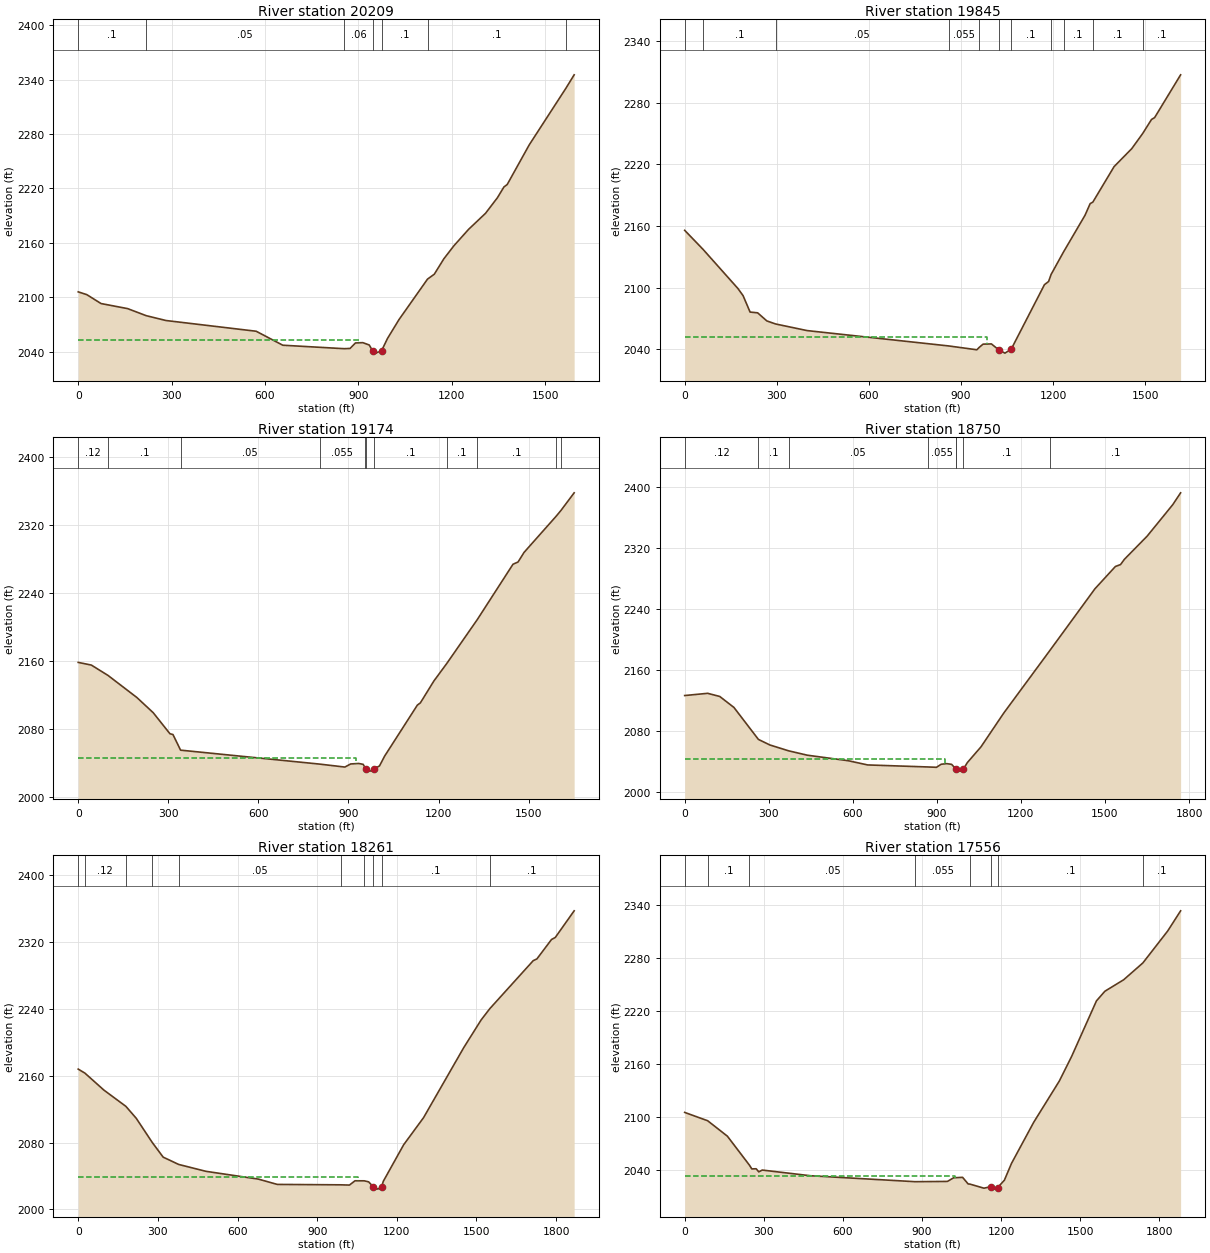
Type RM Length L Ch R = 1 ,20209   ,361.4,364.1,364
XS GIS Cut Line= 3
2185173.50694429307989.7401379312184899.69866318307987.532006632
2183636.64755998308367.330590109
#Sta/Elev= 30
       0 2105.85    27.4 2102.83    73.3 2092.97   158.6 2087.39  218.612079.581
   281.9 2074.25   571.5 2062.43   657.1 2047.01  854.072043.197     873 2043.45
   890.4 2049.51   913.9 2049.85   934.6 2047.28   945.22040.997   955.2  2038.3
  974.472040.997   992.9 2054.25    1030 2075.17 1121.822119.932  1143.6 2125.33
  1174.4 2142.38  1206.5 2156.66  1253.2 2174.62  1308.1 2192.49  1346.1 2209.58
  1367.2 2221.51  1377.7 2224.21  1448.5 2267.97 1566.822330.687  1592.7 2345.17
#Mann= 7 ,-1 , 0
       0      .1       0  218.61     .05       0  854.07     .06       0
   945.2    .045       0  974.47      .1       0 1121.82      .1       0
 1566.82      .1       0
#XS Ineff= 2 , 0
           902.6 2052.74
Permanent Ineff=
       F       F
Bank Sta=945.2,974.47
XS Rating Curve= 0 ,0
Exp/Cntr(USF)=0,0
Exp/Cntr=0.3,0.1

Type RM Length L Ch R = 1 ,19845   ,669.8,671.2,668.2
XS GIS Cut Line= 3
 2185124.9280557307609.9415544542184336.62518186307791.008320996
2183554.94670191307991.948269231
#Sta/Elev= 30
       0 2155.84   59.932137.278   173.5  2099.2   190.3 2092.23   213.1 2076.26
   237.7 2075.53   267.7 2067.64  296.222064.673     399 2058.22  859.972043.292
     952 2039.55  959.712041.896   972.3 2045.03   999.4 2045.25  1023.1 2039.56
  1043.4 2036.29  1063.8 2040.05  1172.2 2102.91  1185.7 2106.01 1193.922112.897
 1234.592134.879  1304.3 2170.42  1321.2 2181.84 1329.842183.275  1399.1 2217.84
  1456.7 2235.35 1492.182250.022  1521.1 2263.77  1531.2 2265.57  1615.9 2307.21
#Mann= 11 ,-1 , 0
       0     .12       0   59.93      .1       0  296.22     .05       0
  859.97    .055       0  959.71     .06       0  1023.1    .045       0
  1063.8      .1       0 1193.92      .1       0 1234.59      .1       0
 1329.84      .1       0 1492.18      .1       0
#XS Ineff= 2 , 0
          984.23 2051.94
Permanent Ineff=
       F       F
Bank Sta=1023.1,1063.8
XS Rating Curve= 0 ,0
Exp/Cntr(USF)=0,0
Exp/Cntr=0.3,0.1

Type RM Length L Ch R = 1 ,19174   ,423.1,423.6,423.3
XS GIS Cut Line= 4
2184821.56595143307013.0918425222184109.75407854307164.541177178
2183673.57999473307282.6716582092183261.63780447307512.874646887
#Sta/Elev= 30
       0 2158.61    43.8 2155.45   99.442143.238   195.3 2117.33   249.8 2099.44
   305.5  2074.7   315.5  2073.8  340.912055.397  803.892039.005   887.9 2035.53
   907.4 2039.16   934.2 2039.75     949 2038.72  954.262035.368  957.132033.177
   972.8 2030.74  984.872033.173  1003.4 2036.92  1020.4  2048.4  1129.4 2108.38
  1139.4 2110.99    1184 2136.53 1227.78 2157.56 1329.112209.044  1447.8 2274.01
  1464.7 2276.67  1484.7 2287.96  1590.1 2329.91 1606.882336.971  1651.5 2358.02
#Mann= 11 ,-1 , 0
       0     .12       0   99.44      .1       0  340.91     .05       0
  803.89    .055       0  954.26      .1       0  957.13    .045       0
  984.87      .1       0 1227.78      .1       0 1329.11      .1       0
  1590.1      .1       0 1606.88      .1       0
#XS Ineff= 2 , 0
          926.52 2046.58
Permanent Ineff=
       F       F
Bank Sta=957.13,984.87
XS Rating Curve= 0 ,0
Exp/Cntr(USF)=0,0
Exp/Cntr=0.3,0.1

Type RM Length L Ch R = 1 ,18750   ,486.9,488.7,486.1
XS GIS Cut Line= 4
2184679.20357685306664.7583728132183988.59461082306770.772907072
2183531.21762016306882.8454147172182970.85508193307097.903469929
#Sta/Elev= 30
       0 2126.83    81.9 2129.75   125.1 2125.64   175.8  2111.2   263.1 2069.25
   304.3 2061.91  370.812054.277   437.6 2048.52   584.4 2041.23   652.8 2035.74
     8682033.066   898.6 2032.64   915.5 2036.68   935.5 2037.41   952.6  2036.5
  967.642030.607  968.952030.109   979.7 2027.61  994.342030.107  1008.7 2038.81
  1057.4 2059.49  1138.4 2103.71 1304.042186.395    1464 2266.96  1537.1 2296.26
  1555.4 2298.76  1569.4 2305.76  1650.2 2336.02  1741.6 2377.32  1769.8 2392.95
#Mann= 8 ,-1 , 0
       0     .12       0   263.1      .1       0  370.81     .05       0
     868    .055       0  967.64      .1       0  968.95    .045       0
  994.34      .1       0 1304.04      .1       0
#XS Ineff= 2 , 0
          928.94 2043.84
Permanent Ineff=
       F       F
Bank Sta=968.95,994.34
XS Rating Curve= 0 ,0
Exp/Cntr(USF)=0,0
Exp/Cntr=0.3,0.1

Type RM Length L Ch R = 1 ,18261   ,703.4,705.7,704.6
XS GIS Cut Line= 3
2184597.42093614306119.540768051 2183731.1307419306331.569836569
2182801.23182711306628.410532495
#Sta/Elev= 30
       0 2167.88   25.242163.066    97.1 2142.68  179.292123.405   218.7 2108.98
  278.932080.105     320 2062.54  378.572053.795   481.2 2045.57   678.1  2036.3
   749.9 2029.91  988.182029.424  1021.7 2029.13  1042.5 2034.26 1077.512034.213
    1094 2032.96 1110.872027.345  1128.5 2024.28 1143.112027.343  1149.1 2033.63
  1225.9 2077.39  1300.7 2109.77  1452.1 2193.56  1517.6 2226.71 1550.37 2240.22
  1713.9 2297.65  1727.7  2299.7  1782.8 2322.98  1796.9 2325.37    1868 2357.26
#Mann= 10 ,-1 , 0
       0      .1       0   25.24     .12       0  179.29      .1       0
  278.93      .1       0  378.57     .05       0  988.18    .055       0
 1077.51      .1       0 1110.87    .045       0 1143.11      .1       0
 1550.37      .1       0
#XS Ineff= 2 , 0
         1051.99 2038.36
Permanent Ineff=
       F       F
Bank Sta=1110.87,1143.11
XS Rating Curve= 0 ,0
Exp/Cntr(USF)=0,0
Exp/Cntr=0.3,0.1

Type RM Length L Ch R = 1 ,17556   ,271.1,271.8,267.1
XS GIS Cut Line= 4
2184325.75531617305637.358495417 2183374.2629256 305762.00815357
2183012.77891696305849.2629142772182505.87030713306061.167333138
#Sta/Elev= 30
       0 2105.56   87.152096.147     162 2078.69   245.82045.867   254.6 2041.71
   271.1 2041.86   281.1 2038.37   294.3 2040.41   476.3 2033.99  874.072027.255
   996.5 2027.56  1020.1 2031.66  1053.9 2032.19  1075.2 2024.66  1081.22024.584
    1135 2019.92  1161.4 2021.62  1177.3 2018.85 1187.032020.632  1212.5 2028.93
  1239.5 2047.92  1323.9 2094.49  1421.1 2141.13  1467.4 2168.75  1561.7 2231.63
  1593.7 2242.54  1664.9 2255.51  1737.7 2274.51    1832 2310.68  1880.9 2333.43
#Mann= 8 ,-1 , 0
       0     .12       0   87.15      .1       0   245.8     .05       0
  874.07    .055       0  1081.2      .1       0  1161.4    .045       0
 1187.03      .1       0  1737.7      .1       0
#XS Ineff= 2 , 0
         1024.26 2033.56
Permanent Ineff=
       F       F
Bank Sta=1161.4,1187.03
XS Rating Curve= 0 ,0
Exp/Cntr(USF)=0,0
Exp/Cntr=0.3,0.1

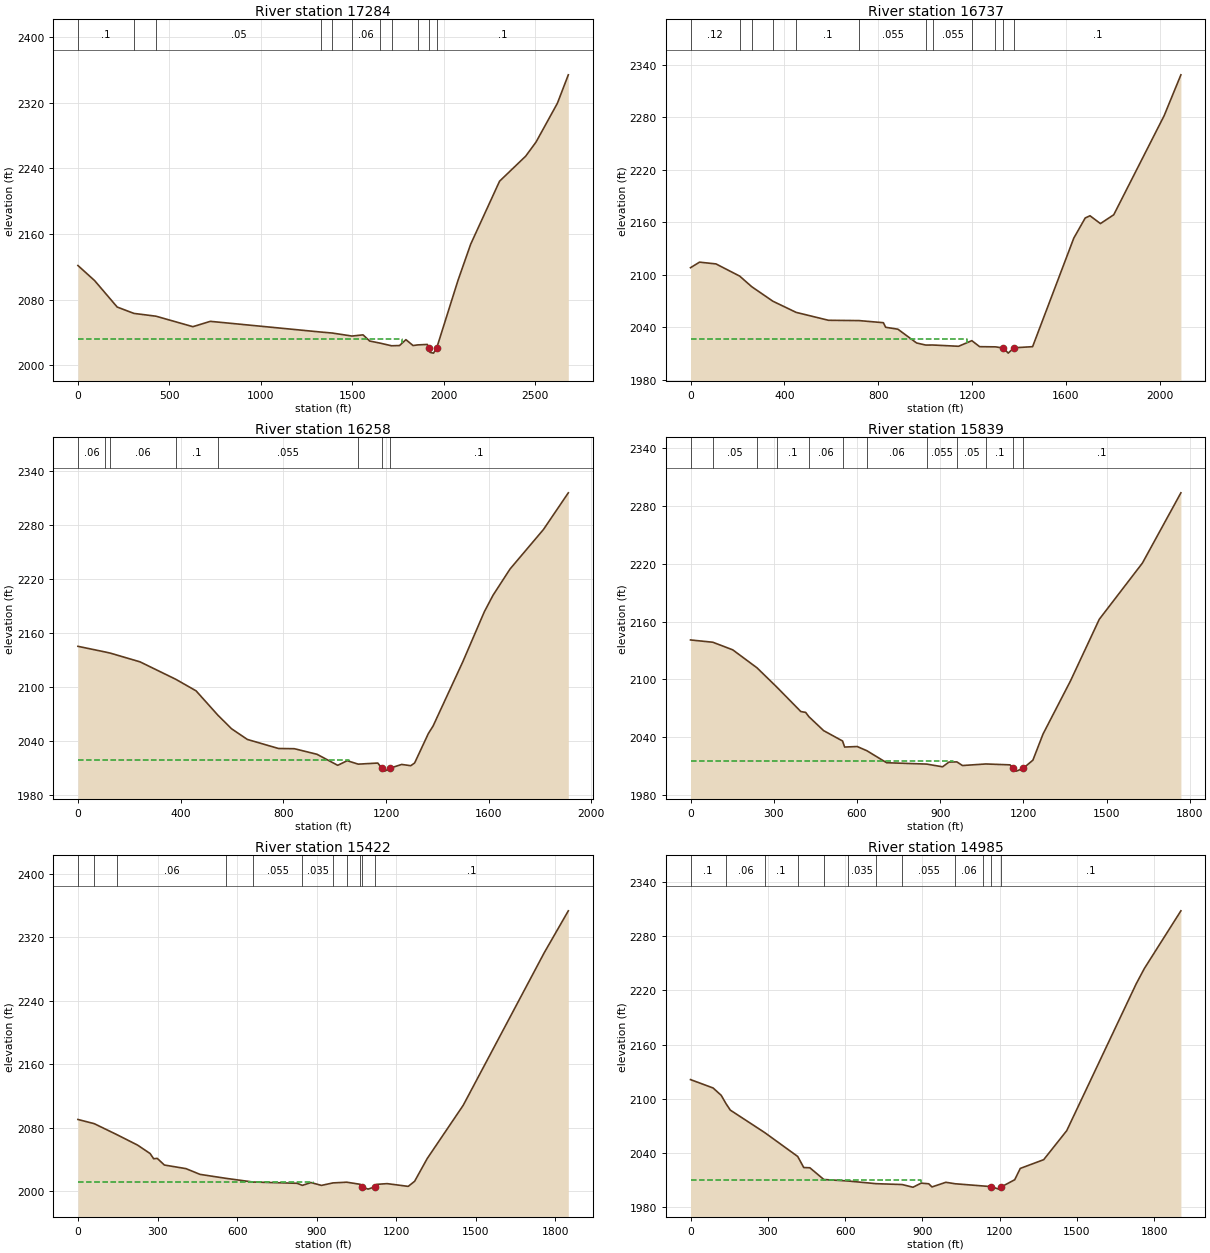
Type RM Length L Ch R = 1 ,17284   ,538.9,547.2,547.1
XS GIS Cut Line= 4
2184475.33490595304286.9871987582183203.90839279305500.243871449
2182846.57937275305687.2183586782182393.68561479 305940.67266359
#Sta/Elev= 30
       0 2121.51      91 2103.16   214.6 2070.83  306.012063.081  426.452059.671
   628.2 2046.89   723.5  2053.4 1328.652040.317 1390.012039.126 1497.692035.446
  1557.9 2036.92  1594.2 2029.39 1650.232026.854 1713.722023.596  1757.4 2023.88
  1792.3 2031.06  1831.2 2023.87 1856.822024.657  1909.3 2025.21  1916.3 2020.41
  1924.1 2015.46    1943 2014.62  1960.1 2020.63  2076.7 2103.28  2146.2 2147.56
    2304 2224.37  2446.8 2254.93  2503.2 2272.11    2620 2319.46  2679.7 2354.16
#Mann= 11 ,-1 , 0
       0      .1       0  306.01    .055       0  426.45     .05       0
 1328.65     .06       0 1390.01    .055       0 1497.69     .06       0
 1650.23    .055       0 1713.72     .06       0 1856.82      .1       0
  1916.3    .045       0  1960.1      .1       0
#XS Ineff= 2 , 0
         1770.07 2031.36
Permanent Ineff=
       F       F
Bank Sta=1916.3,1960.1
XS Rating Curve= 0 ,0
Exp/Cntr(USF)=0,0
Exp/Cntr=0.3,0.1

Type RM Length L Ch R = 1 ,16737   ,483.9,478.2,468.4
XS GIS Cut Line= 4
2183802.22675193304241.2823241022182962.91905369305059.815079307
2182588.97007923305184.4647374612182165.16124151305491.933894238
#Sta/Elev= 30
       0 2108.22    38.4 2114.54   108.5 2112.53  209.57 2098.63  261.222086.468
  351.232069.942  450.072057.244     588 2048.21  719.06 2047.85     822 2045.45
   831.7 2040.23   883.8 2038.05   963.7 2022.32 1002.262019.955 1033.782019.989
  1142.5 2018.55    11992024.951  1232.4  2018.1 1299.632017.896  1333.6 2016.58
  1354.1 2010.74  1378.3 2016.82  1458.1 2018.12  1633.7 2142.02  1682.3 2164.95
  1702.6 2167.46  1747.2 2158.54  1803.9 2168.61  2018.8  2281.7  2090.1 2328.26
#Mann= 12 ,-1 , 0
       0     .12       0  209.57     .05       0  261.22      .1       0
  351.23     .05       0  450.07      .1       0  719.06    .055       0
 1002.26     .05       0 1033.78    .055       0    1199     .06       0
 1299.63      .1       0  1333.6    .045       0  1378.3      .1       0
#XS Ineff= 2 , 0
          1178.6 2026.92
Permanent Ineff=
       F       F
Bank Sta=1333.6,1378.3
XS Rating Curve= 0 ,0
Exp/Cntr(USF)=0,0
Exp/Cntr=0.3,0.1

Type RM Length L Ch R = 1 ,16258   ,414.6,419.4,422.2
XS GIS Cut Line= 4
2183578.95168524304031.0022835032182712.61661257304578.161276767
2182456.13583447304828.942482014 2182005.8695796305102.521978646
#Sta/Elev= 30
       0 2145.32  105.612139.066  126.772137.713   241.8 2128.07  381.342108.665
   460.2 2095.85  544.68 2068.95   598.1 2053.76     660 2041.83   781.3 2031.78
   843.1 2031.53   931.1 2025.35    1012 2013.07  1048.8 2018.21 1091.952014.381
  1168.1 2015.59 1183.442009.886  1195.6 2006.62 1215.532009.883  1261.2 2014.05
  1296.6 2012.65  1311.6 2015.74  1364.9 2048.35  1383.4 2056.75  1498.9 2127.97
  1583.3 2183.88  1616.9 2202.06  1683.1 2231.21  1813.3 2275.13  1910.2  2315.9
#Mann= 8 ,-1 , 0
       0     .06       0  105.61     .05       0  126.77     .06       0
  381.34      .1       0  544.68    .055       0 1091.95      .1       0
 1183.44    .045       0 1215.53      .1       0
#XS Ineff= 2 , 0
          1054.9 2018.91
Permanent Ineff=
       F       F
Bank Sta=1183.44,1215.53
XS Rating Curve= 0 ,0
Exp/Cntr(USF)=0,0
Exp/Cntr=0.3,0.1

Type RM Length L Ch R = 1 ,15839   ,412.4,417,415.9
XS GIS Cut Line= 3
2183385.16620845303899.9121080332182478.93412586304310.281352982
2181800.68495713304680.753588005
#Sta/Elev= 30
       0 2140.91    80.52138.534   152.2 2130.66  239.872111.933  311.162091.946
   397.6 2066.59   415.1 2065.69   426.9 2061.19   479.9 2046.75  548.062036.018
   555.5 2029.72   600.9 2030.26  636.342025.802   706.8 2013.44  850.942012.037
   908.5 2009.21   931.6 2014.12   960.22014.293   980.2 2010.53 1064.712012.149
  1151.9 2011.22 1162.662007.522  1174.4 2004.72 1198.622007.526  1234.2 2016.12
  1270.6 2043.19  1369.8 2098.49  1473.4 2162.35    1629 2220.78  1767.6 2293.66
#Mann= 12 ,-1 , 0
       0     .12       0    80.5     .05       0  239.87     .06       0
  311.16      .1       0   426.9     .06       0  548.06    .055       0
  636.34     .06       0  850.94    .055       0   960.2     .05       0
 1064.71      .1       0 1162.66    .045       0 1198.62      .1       0
#XS Ineff= 2 , 0
          946.24 2015.45
Permanent Ineff=
       F       F
Bank Sta=1162.66,1198.62
XS Rating Curve= 0 ,0
Exp/Cntr(USF)=0,0
Exp/Cntr=0.3,0.1

Type RM Length L Ch R = 1 ,15422   ,432.4,436.7,430.4
XS GIS Cut Line= 4
2183185.68115883303734.6244954842182359.24309608303939.809117958
2181988.77086106304105.0967305072181510.00674195304452.770674144
#Sta/Elev= 30
       0 2090.28    61.32085.003  145.762071.311   224.9 2057.93     272 2047.33
   285.5 2040.74     299 2041.17     326 2032.78   407.2 2028.26   460.3    2021
  559.642015.925  659.312011.373   826.3 2009.74  846.112007.136   878.7 2010.65
   918.2 2007.08  961.622010.231 1013.58 2011.12 1064.372008.455 1071.072005.315
  1093.8 2002.38 1120.07 2005.31  1126.5  2008.4  1165.8 2009.31  1245.3 2005.85
  1269.5 2012.31  1316.9 2040.98  1452.7  2108.2    1758  2300.6  1848.9 2353.54
#Mann= 11 ,-1 , 0
       0     .12       0    61.3    .055       0  145.76     .06       0
  559.64    .035       0  659.31    .055       0  846.11    .035       0
  961.62    .055       0 1013.58     .05       0 1064.37      .1       0
 1071.07    .045       0 1120.07      .1       0
#XS Ineff= 2 , 0
          887.38 2011.56
Permanent Ineff=
       F       F
Bank Sta=1071.07,1120.07
XS Rating Curve= 0 ,0
Exp/Cntr(USF)=0,0
Exp/Cntr=0.3,0.1

Type RM Length L Ch R = 1 ,14985   ,493.9,511.6,499.2
XS GIS Cut Line= 3
2182957.69824497 303267.259522072182045.76658952303614.933465707
2181247.82639101304087.998011968
#Sta/Elev= 30
       0 2121.12    87.6 2111.83   119.3 2103.62  137.582094.522   154.4  2087.3
  288.242062.318  416.132035.858   439.6 2023.58   463.3 2023.33  517.552010.325
  611.552008.642  720.392005.673  821.812004.731   863.6 2001.74   895.2 2006.28
   924.9 2005.56   937.3 2002.07   991.2 2007.22 1027.19 2005.59 1133.912003.174
  1165.1 2002.43  1197.2 1999.64 1206.542002.138  1258.5 2010.06  1280.1 2022.61
    1371 2032.31  1460.4 2064.47  1730.2 2227.41  1761.7 2244.31  1903.6 2308.29
#Mann= 12 ,-1 , 0
       0      .1       0  137.58     .06       0  288.24      .1       0
  416.13    .035       0  517.55     .02       0  611.55    .035       0
  720.39     .06       0  821.81    .055       0 1027.19     .06       0
 1133.91      .1       0  1165.1    .045       0 1206.54      .1       0
#XS Ineff= 2 , 0
          894.28 2009.36
Permanent Ineff=
       F       F
Bank Sta=1165.1,1206.54
XS Rating Curve= 0 ,0
Exp/Cntr(USF)=0,0
Exp/Cntr=0.3,0.1

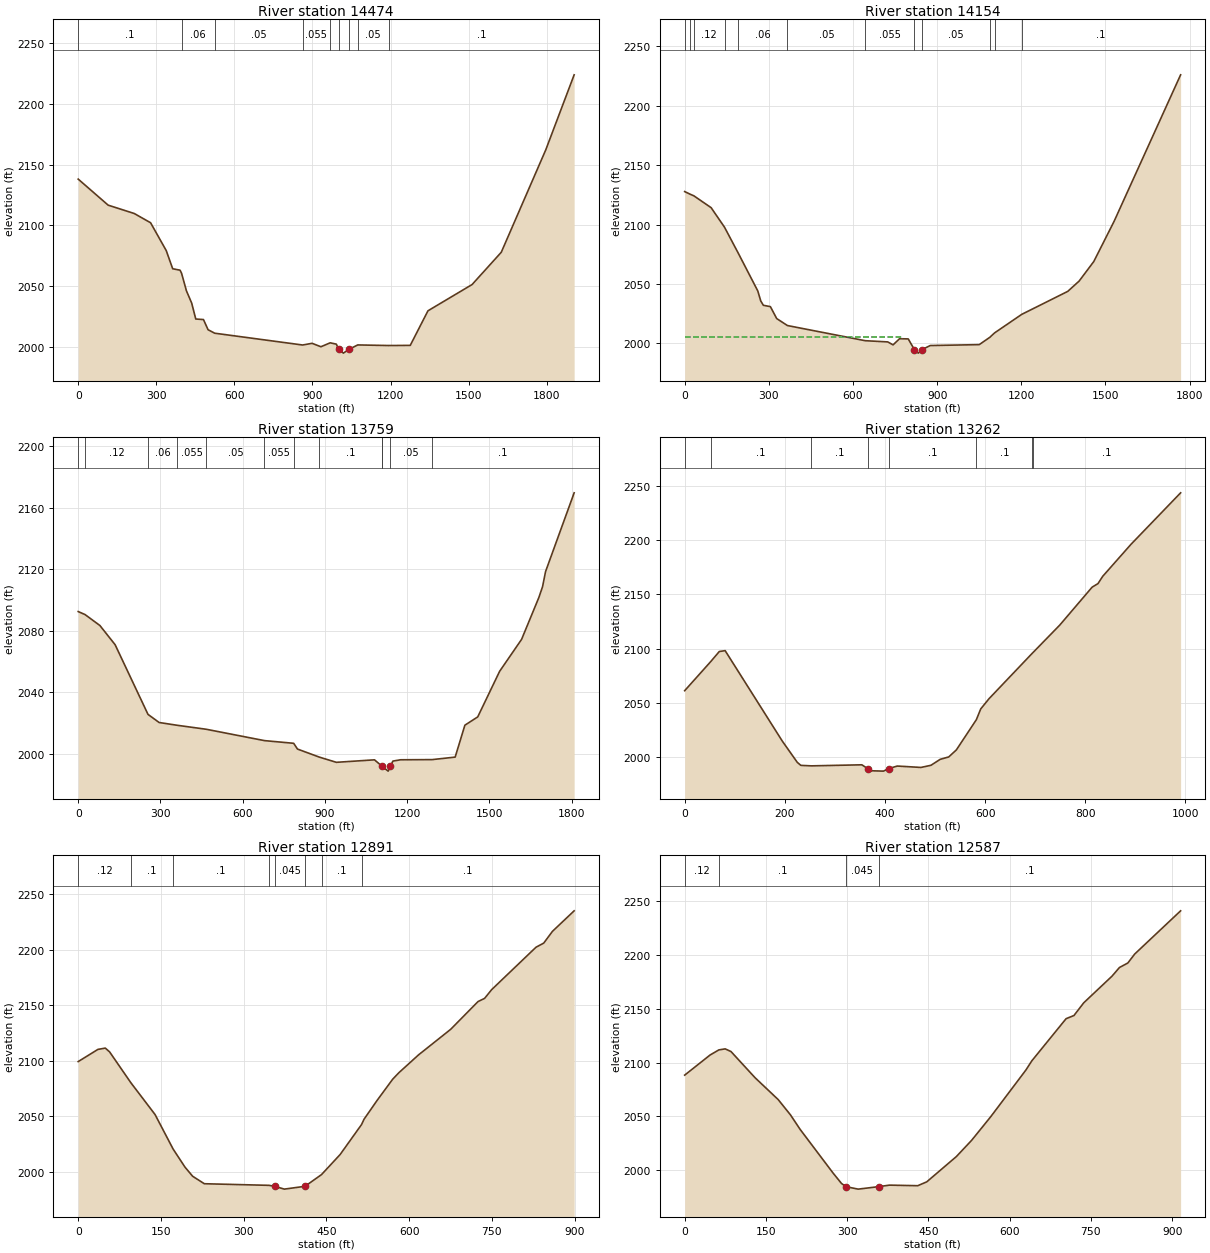
Type RM Length L Ch R = 1 ,14474   ,318.8,319.6,317.9
XS GIS Cut Line= 3
2182838.00721519302936.6842969732182068.56488091303250.160803531
2181133.83493408303780.221078256
#Sta/Elev= 30
       0 2138.16   115.1 2116.69     215 2109.85     278 2102.22   338.2 2079.27
     363 2064.28   391.4  2063.1  397.192060.507   415.8 2046.09     436 2035.98
   451.6 2022.87   481.3  2022.4   498.9 2014.04  524.352011.171  862.072001.443
   898.6 2002.84   932.5 2000.01  968.012003.246   991.7 2002.16 1000.861997.773
  1018.9 1994.75 1039.261997.772 1073.94  2001.5 1193.07 2001.01  1275.7 2001.14
  1343.8 2029.64  1513.3 2051.28  1625.4 2077.87  1796.5 2162.35  1905.4 2224.11
#Mann= 9 ,-1 , 0
       0      .1       0  397.19     .06       0  524.35     .05       0
  862.07    .055       0  968.01     .06       0 1000.86    .045       0
 1039.26     .06       0 1073.94     .05       0 1193.07      .1       0
#XS Ineff= 2 , 0
          969.96 2002.84
Permanent Ineff=
       F       F
Bank Sta=1000.86,1039.26
XS Rating Curve= 0 ,0
Exp/Cntr(USF)=0,0
Exp/Cntr=0.3,0.1

Type RM Length L Ch R = 1 ,14154   ,402.1,394.9,387.5
XS GIS Cut Line= 4
2182330.74523185302486.4180420992181823.48324851303027.877462517
 2181601.1999075 303170.366783682181048.34134139303694.727485559
#Sta/Elev= 30
       0 2127.76   20.34 2125.45   32.772124.179    94.3 2114.21  141.962097.814
  191.112075.916   260.6  2044.2   271.2 2035.76   280.5 2032.12   305.6 2030.97
     328 2020.95  366.252015.076  643.792002.316   723.8 2001.31   742.9 1998.82
   766.1 2003.99     797 2003.83  819.011994.797   832.7 1991.87   845.91994.799
   875.3 1998.25  1050.1 1999.02  1087.92005.181 1104.542008.839 1201.682024.494
  1365.5 2043.78  1406.2 2052.47  1458.5 2068.94  1530.5 2102.55    1768 2225.96
#Mann= 12 ,-1 , 0
       0     .12       0   20.34      .1       0   32.77     .12       0
  141.96      .1       0  191.11     .06       0  366.25     .05       0
  643.79    .055       0  819.01    .045       0   845.9     .05       0
  1087.9      .1       0 1104.54     .05       0 1201.68      .1       0
#XS Ineff= 2 , 0
          774.19 2005.03
Permanent Ineff=
       F       F
Bank Sta=819.01,845.9
XS Rating Curve= 0 ,0
Exp/Cntr(USF)=0,0
Exp/Cntr=0.3,0.1

Type RM Length L Ch R = 1 ,13759   ,488,497.1,497.1
XS GIS Cut Line= 4
2182222.45334777302275.5338467782181504.30716911302691.602664573
2181293.42297379303187.4655022192180957.14817584303472.444144545
#Sta/Elev= 30
       0 2092.37      252090.405    79.1  2083.3   134.7  2070.8  254.642025.474
   295.2  2020.2  360.942018.391  467.242015.791  679.39 2008.41  786.162006.662
   800.1 2002.92   879.61997.689     942 1994.29  1081.1 1995.91 1107.331991.933
 1107.421991.918    1131 1988.56 1139.411991.917  1148.2 1995.09  1176.1 1995.94
 1291.351996.051  1375.4 1997.68  1410.9 2018.44  1457.8 2023.84  1537.7  2053.5
  1617.8 2074.27  1680.7 2101.45  1694.3 2108.53  1705.2 2118.34  1809.6 2169.61
#Mann= 12 ,-1 , 0
       0      .1       0      25     .12       0  254.64     .06       0
  360.94    .055       0  467.24     .05       0  679.39    .055       0
  786.16      .1       0   879.6      .1       0 1107.33     .05       0
 1107.42    .045       0 1139.41     .05       0 1291.35      .1       0
Bank Sta=1107.42,1139.41
XS Rating Curve= 0 ,0
Exp/Cntr(USF)=0,0
Exp/Cntr=0.3,0.1

Type RM Length L Ch R = 1 ,13262   ,355.2,370.9,373.9
XS GIS Cut Line= 4
2181223.11304315302415.8687294052181048.70611405302615.923736317
2180879.42880051 302872.404514412180546.00378899303123.755676941
#Sta/Elev= 30
       0 2061.08   51.642087.778    69.1 2097.28    80.8 2098.09   194.7 2014.67
   224.9 1994.83   231.9 1992.08  252.971991.614   353.8 1992.59  365.31 1989.15
     371  1987.1     397 1986.75   407.61989.148   424.6 1991.44   471.8 1990.16
   491.8 1992.15   510.2 1997.64   527.3 1999.88   542.5 2006.36  582.432034.282
   591.2 2044.26   607.6 2053.63  693.862095.563  694.722095.962   748.9 2121.67
   813.6 2156.77   825.3 2160.06   834.7 2166.76   891.1 2196.31   990.3 2243.95
#Mann= 8 ,-1 , 0
       0      .1       0   51.64      .1       0  252.97      .1       0
  365.31    .045       0   407.6      .1       0  582.43      .1       0
  693.86     .12       0  694.72      .1       0
Bank Sta=365.31,407.6
XS Rating Curve= 0 ,0
Exp/Cntr(USF)=0,0
Exp/Cntr=0.3,0.1

Type RM Length L Ch R = 1 ,12891   ,302.6,304.2,304.5
XS GIS Cut Line= 3
2181058.96534517302256.8506469872180674.24417803302528.720271765
2180320.30070426302769.812203173
#Sta/Elev= 30
       0 2099.16    35.7 2110.12    49.1  2111.3    56.9 2107.91   95.422080.152
   139.3 2051.52  172.172020.336   193.7 2004.06   207.5  1995.9   228.7 1989.17
  346.061987.713  356.531986.856   373.7 1984.31  411.331986.856   441.21997.408
   474.9 2015.43  513.712042.411   518.4 2047.33     542 2064.21   570.3 2083.32
   581.7 2089.24   617.2 2105.22   675.5 2128.25     725  2153.2   736.9 2156.07
   749.8 2163.99   830.1 2202.12   844.1 2205.83     860 2216.45   899.3 2234.91
#Mann= 8 ,-1 , 0
       0     .12       0   95.42      .1       0  172.17      .1       0
  346.06      .1       0  356.53    .045       0  411.33      .1       0
   441.2      .1       0  513.71      .1       0
Bank Sta=356.53,411.33
XS Rating Curve= 0 ,0
Exp/Cntr(USF)=0,0
Exp/Cntr=0.3,0.1

Type RM Length L Ch R = 1 ,12587   ,508.9,509.2,497.3
XS GIS Cut Line= 3
2180894.81764719302036.2771778272180469.05955556302297.887571482
2180145.89377516302559.497965137
#Sta/Elev= 30
       0 2088.32    46.9 2107.02    63.12111.764    74.8 2112.72    85.5 2110.24
     130 2085.88   172.6 2065.62   195.4 2051.34   213.1 2037.94   274.1 1997.24
   289.5 1987.66  297.891984.691   320.3 1982.41  357.981984.692   378.1 1986.12
   430.2 1985.59   446.9 1989.19   501.7 2012.74   529.7 2027.75   564.7 2049.52
     630 2093.13   640.8 2101.59   704.1 2140.77   718.6 2143.72   736.6 2155.48
   788.8 2180.25   802.6 2188.32   818.1 2192.52   830.7 2200.81   915.5 2240.98
#Mann= 4 ,-1 , 0
       0     .12       0    63.1      .1       0  297.89    .045       0
  357.98      .1       0
Bank Sta=297.89,357.98
XS Rating Curve= 0 ,0
Exp/Cntr(USF)=0,0
Exp/Cntr=0.3,0.1