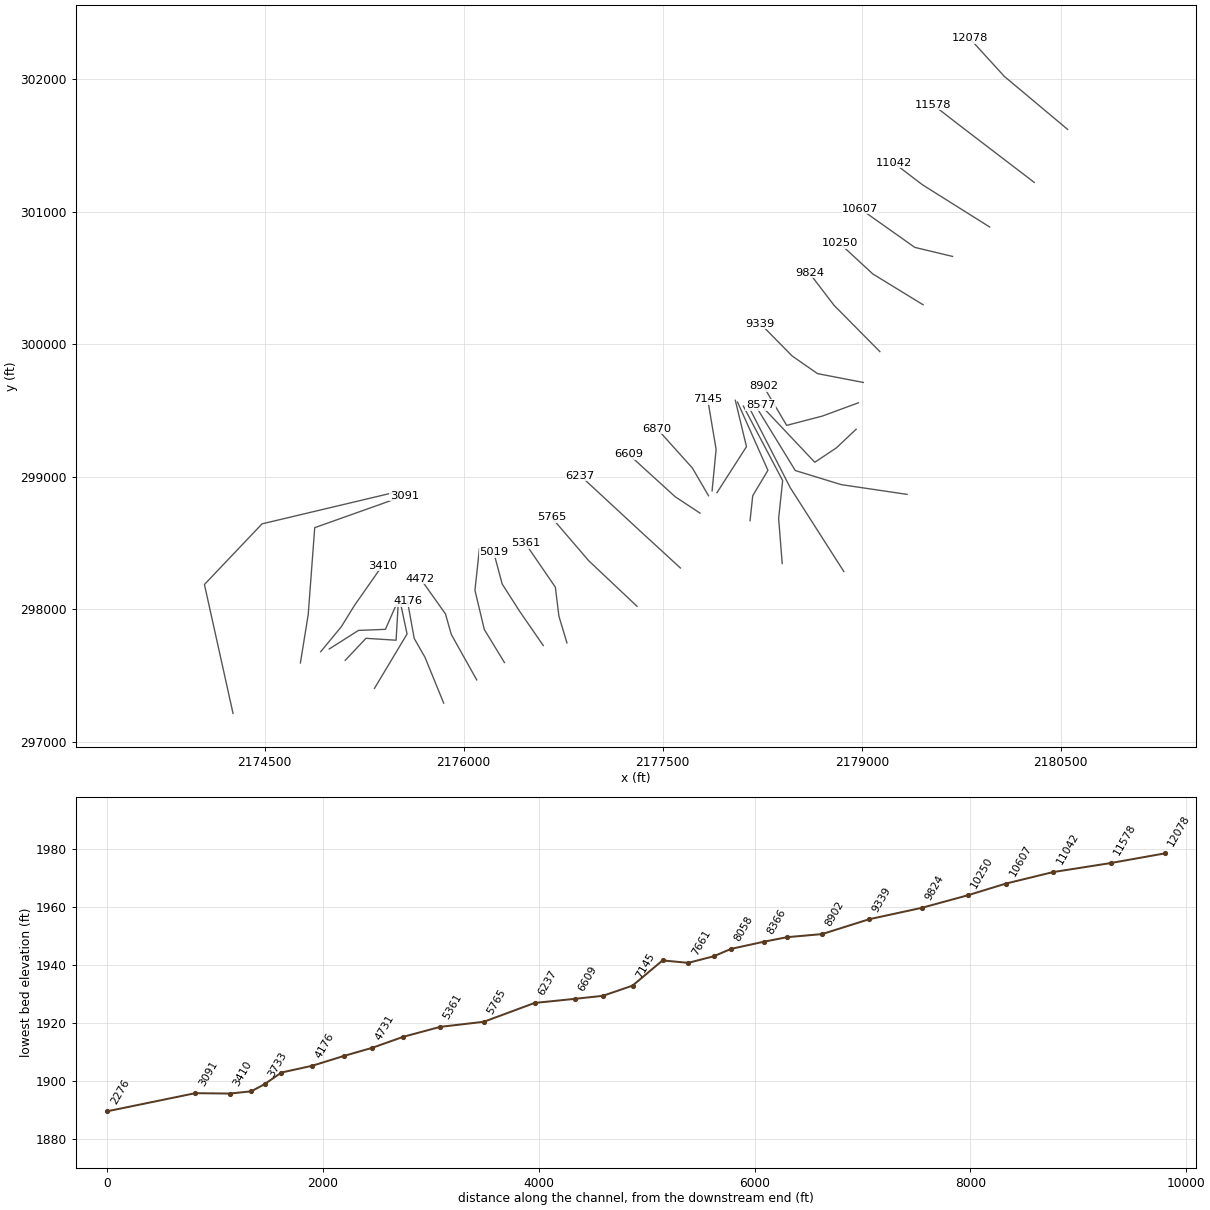
HEC-RAS study HOWARDCK.prj: HOWARDCK

--- HOWARDCK.g01 (geometry) --- (continued)

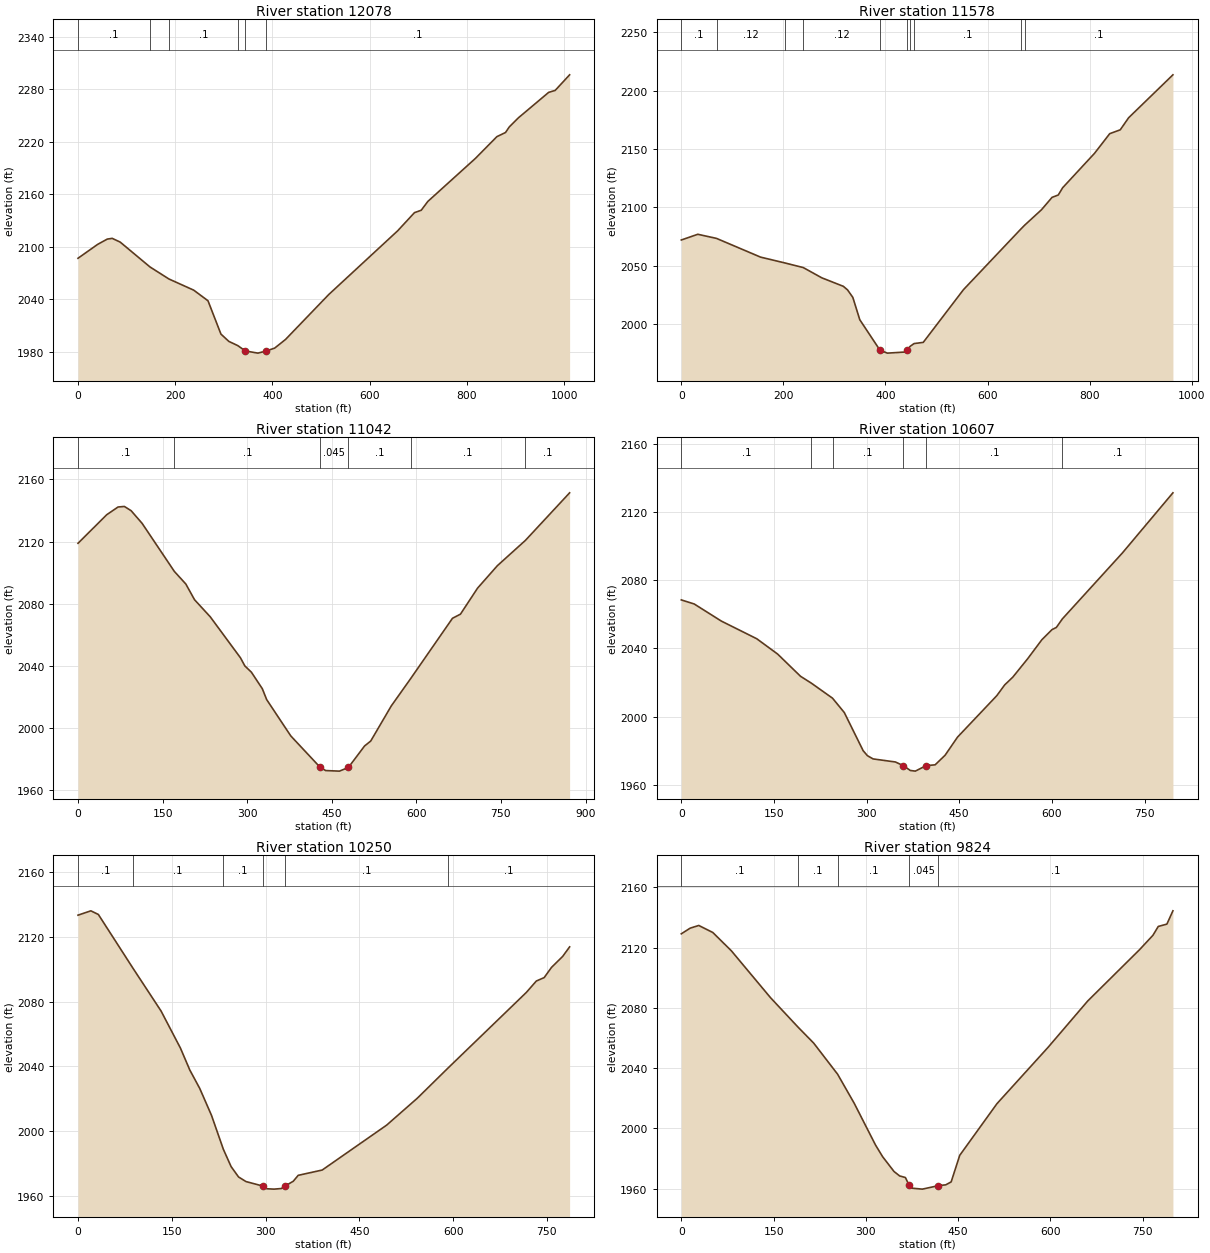
Type RM Length L Ch R = 1 ,12078   ,492.8,500.3,492.9
XS GIS Cut Line= 3
2180551.13340455301620.7783173172180074.07915729302020.888331142
2179812.46876364302308.146802606
#Sta/Elev= 30
       0 2086.76    40.4 2102.61    60.3 2108.67    70.4 2109.48    86.8 2105.23
  148.152076.813  187.182063.059   238.1 2050.32   267.4 2038.21     294 2000.19
   310.3 1991.81  328.55 1987.05  344.191980.933   370.1 1978.42  387.371980.931
   404.4  1984.1   426.8 1993.99   515.7  2045.3   657.5  2118.1   692.1 2138.87
     706  2141.6   719.6 2151.67   817.5 2200.83   861.6 2225.65   879.4 2230.42
   887.1 2236.75   905.7 2247.07   968.1 2276.21   981.5 2278.46  1011.2 2296.26
#Mann= 6 ,-1 , 0
       0      .1       0  148.15      .1       0  187.18      .1       0
  328.55      .1       0  344.19    .045       0  387.37      .1       0
Bank Sta=344.19,387.37
XS Rating Curve= 0 ,0
Exp/Cntr(USF)=0,0
Exp/Cntr=0.3,0.1

Type RM Length L Ch R = 1 ,11578   ,526.7,535.4,530.3
XS GIS Cut Line= 3
2180299.78224202301220.6683034922179741.22410306 301648.13626698
2179536.03948058301807.724306682
#Sta/Elev= 30
       0 2071.98    32.3 2076.88      692073.351   155.3 2057.32  203.382052.283
  238.992048.369   275.2 2039.61   317.4 2032.34   325.7 2029.29   336.1 2022.83
   349.7 2003.74  389.331977.588   403.9  1975.1   437.2 1976.01  441.361977.585
  448.861981.066  456.141983.284   474.1 1984.31   552.9 2029.45   665.12081.239
  673.082084.783   705.8  2097.9   726.5 2108.51   738.6  2110.5   747.3 2116.76
   809.7 2146.21   839.5 2163.04   860.1 2166.34   876.5 2176.66   963.3 2213.43
#Mann= 10 ,-1 , 0
       0      .1       0      69     .12       0  203.38      .1       0
  238.99     .12       0  389.33    .045       0  441.36     .12       0
  448.86      .1       0  456.14      .1       0   665.1      .1       0
  673.08      .1       0
Bank Sta=389.33,441.36
XS Rating Curve= 0 ,0
Exp/Cntr(USF)=0,0
Exp/Cntr=0.3,0.1

Type RM Length L Ch R = 1 ,11042   ,431.6,435.3,428.3
XS GIS Cut Line= 3
2179963.50744407300884.3935055482179456.24546073301203.569584952
2179239.66169257301368.857197501
#Sta/Elev= 30
       0 2118.84    50.9 2137.25      71 2142.24    82.3 2142.59    94.2 2139.86
   113.7  2131.7   170.92100.706   191.2 2092.61   206.7 2082.46   234.6 2071.43
   288.1 2045.03   295.9  2039.8   307.5 2035.75   326.9 2025.09   334.6 2018.08
   377.4 1994.66  429.551974.389   439.3 1972.34   463.7 1971.98  479.62 1974.39
   508.2  1988.2   519.1 1991.37   555.6 2014.03  590.062031.688   664.1 2070.51
   678.2 2073.16   708.6 2089.95   743.7 2104.41  793.542120.762   871.8 2151.38
#Mann= 6 ,-1 , 0
       0      .1       0   170.9      .1       0  429.55    .045       0
  479.62      .1       0  590.06      .1       0  793.54      .1       0
Bank Sta=429.55,479.62
XS Rating Curve= 0 ,0
Exp/Cntr(USF)=0,0
Exp/Cntr=0.3,0.1

Type RM Length L Ch R = 1 ,10607   ,351.7,356.9,353.8
XS GIS Cut Line= 3
2179684.22837459300662.1101645342179399.24973227300730.505038692
2178988.88048732301021.183253864
#Sta/Elev= 30
       0 2068.44    20.9 2066.05    64.8 2056.03   122.2 2045.66   155.9 2036.71
     193 2023.67  210.622019.611  244.832010.817   263.9 2002.41   294.4 1980.06
   301.3 1977.11   310.5  1975.2   346.7  1973.4  359.441971.251   370.8 1968.43
   378.9 1968.04  396.421971.253     411 1971.74   427.1 1977.35   447.2 1987.96
   510.8 2012.28   523.6 2018.59   536.7 2023.13   560.8 2033.94   583.9 2045.13
   600.2 2051.01   607.3 2052.31  617.15 2057.37   714.1 2095.93     796 2131.23
#Mann= 6 ,-1 , 0
       0      .1       0  210.62      .1       0  244.83      .1       0
  359.44    .045       0  396.42      .1       0  617.15      .1       0
Bank Sta=359.44,396.42
XS Rating Curve= 0 ,0
Exp/Cntr(USF)=0,0
Exp/Cntr=0.3,0.1

Type RM Length L Ch R = 1 ,10250   ,422.6,425.9,415.2
XS GIS Cut Line= 3
2179461.94503358300297.3375023572179082.78379975300530.089248818
2178832.23798686300761.937612983
#Sta/Elev= 30
       0 2133.42    20.6 2136.11    32.6 2133.84   87.852100.656   132.8 2074.18
   163.8 2051.25   178.8 2037.67   194.8  2026.2   213.5 2009.63  232.54 1988.58
   244.9  1977.9   256.8 1971.49   268.7 1968.64  295.791965.859   302.1 1964.19
   313.6 1963.97   325.1 1964.34  331.18 1965.86   344.4 1968.87   352.2  1972.5
   390.6 1975.78   493.6 2003.53   542.8 2020.23  591.842038.868   717.1 2085.64
   733.1  2092.7   745.6  2094.8   757.3  2101.1   775.2 2107.91   786.3 2113.81
#Mann= 6 ,-1 , 0
       0      .1       0   87.85      .1       0  232.54      .1       0
  295.79    .045       0  331.18      .1       0  591.84      .1       0
Bank Sta=295.79,331.18
XS Rating Curve= 0 ,0
Exp/Cntr(USF)=0,0
Exp/Cntr=0.3,0.1

Type RM Length L Ch R = 1 ,9824    ,479.1,485.5,487.5
XS GIS Cut Line= 3
 2179135.9676539299943.8203566382178791.10359967300292.839399467
2178604.12911244300537.983727168
#Sta/Elev= 30
       0 2129.17    14.4 2132.92    28.4 2134.72    51.2 2130.05    81.3 2117.92
   145.1 2086.72  189.642067.252   215.2 2056.59   254.12035.917   281.1  2016.6
   315.6 1988.99   327.2 1981.19   345.7 1971.38   354.9 1968.41   364.2 1967.37
  369.92 1962.49   373.4 1960.34   391.8 1959.66   417.7 1961.95   429.9 1962.52
   438.6 1964.47   452.5 1982.08     513 2016.38   596.2 2053.85   660.5 2084.55
   744.8 2118.65   766.5 2128.17   775.2 2134.06   789.2 2135.61     799 2144.43
#Mann= 5 ,-1 , 0
       0      .1       0  189.64      .1       0   254.1      .1       0
  369.92    .045       0   417.7      .1       0
Bank Sta=369.92,417.7
XS Rating Curve= 0 ,0
Exp/Cntr(USF)=0,0
Exp/Cntr=0.3,0.1

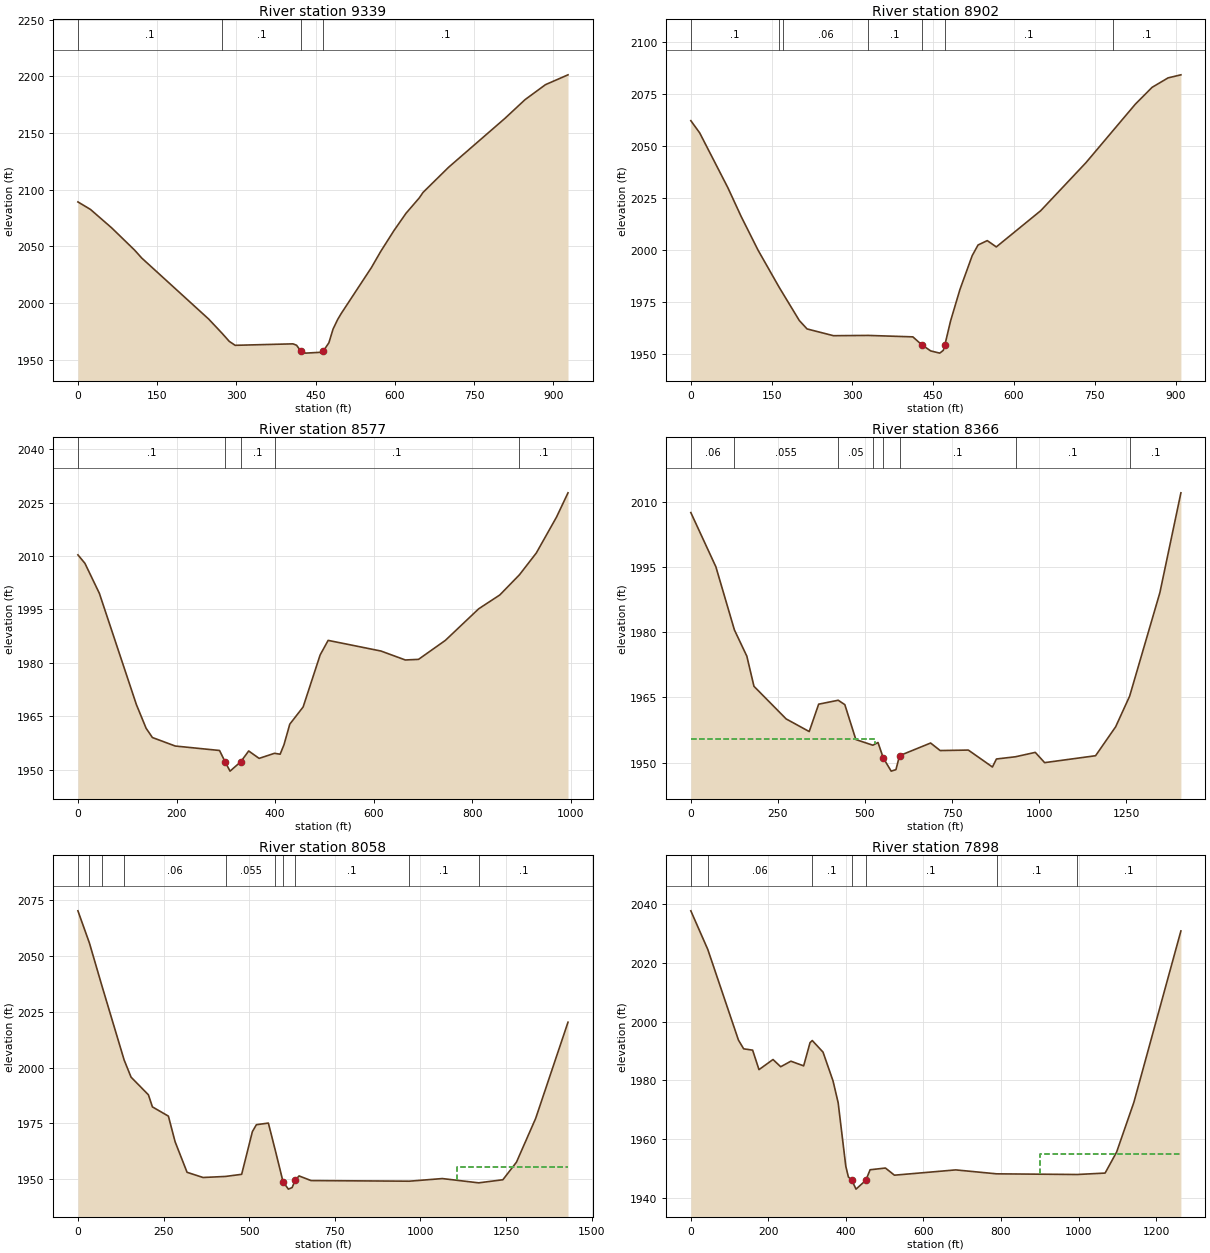
Type RM Length L Ch R = 1 ,9339    ,411.4,437.1,449.9
XS GIS Cut Line= 4
2179011.31799574299711.1409947522178666.45394152299777.620812434
2178475.32446569299910.5804477972178234.33512659300155.724775498
#Sta/Elev= 30
       0 2089.16    23.7 2082.57    63.8 2066.31   107.3 2046.66   120.6 2039.74
   247.6 1985.78  273.291973.062   286.5 1966.13   297.7 1962.64   407.1 1963.94
   413.9  1962.7  421.981957.591   431.1 1955.75   459.1 1956.48   464.51957.588
   475.1 1964.86     483 1976.96   491.7 1985.41   498.4 1990.66   555.8 2031.37
     573  2045.3   598.2  2063.8   621.2 2079.18   646.3 2092.74   653.4 2097.58
   701.9 2119.81   808.7 2163.01   846.7  2179.5   885.2 2192.64   927.8 2201.31
#Mann= 4 ,-1 , 0
       0      .1       0  273.29      .1       0  421.98    .045       0
   464.5      .1       0
Bank Sta=421.98,464.5
XS Rating Curve= 0 ,0
Exp/Cntr(USF)=0,0
Exp/Cntr=0.3,0.1

Type RM Length L Ch R = 1 ,8902    ,310.1,324.7,325
XS GIS Cut Line= 4
 2178973.9230983299557.4064163632178703.84883897299457.686689841
2178433.77457963299387.0518835542178259.26505822299682.056074516
#Sta/Elev= 30
       0 2062.11    16.4 2056.28    68.9  2029.9    93.4 2016.18   124.9 1999.97
  163.791982.305  170.591979.395   201.4 1966.27   215.8 1962.23   264.8 1958.99
   329.81959.119   412.2 1958.43  428.561954.671   445.2  1951.7   462.1 1950.63
   468.7 1951.96  471.711954.671   482.1 1965.96   499.5 1981.08   522.4 1997.42
   533.2 2002.49   550.3 2004.59   567.1 2001.57   649.6 2018.95   733.5 2041.96
   784.52057.575   825.2 2070.03   856.2 2078.08     886 2082.64   909.8  2084.1
#Mann= 7 ,-1 , 0
       0      .1       0  163.79      .1       0  170.59     .06       0
   329.8      .1       0  428.56    .045       0  471.71      .1       0
   784.5      .1       0
Bank Sta=428.56,471.71
XS Rating Curve= 0 ,0
Exp/Cntr(USF)=0,0
Exp/Cntr=0.3,0.1

Type RM Length L Ch R = 1 ,8577    ,225.7,211.1,188.8
XS GIS Cut Line= 4
2178957.30314388299357.9669633182178807.72355409299216.697350745
2178645.67899849299108.6676470122178238.49011519299540.786461943
#Sta/Elev= 30
       0 2010.31    14.2 2007.94    43.5 1999.51   118.6 1968.26   138.3 1961.61
   151.1    1959   197.5 1956.61   287.3 1955.36  298.551952.186   308.6 1949.56
   330.31952.183   346.4 1955.22   367.6 1953.14  398.86 1954.57   410.2 1954.31
     418 1956.96   429.8 1962.75   456.9 1967.59   491.4  1982.2   507.6 1986.29
   614.7  1983.3   664.3 1980.78     691 1980.96   745.4 1986.29     813 1995.16
   855.8 1999.04  895.782004.731   929.9 2010.84   970.8  2020.9   994.2 2027.74
#Mann= 5 ,-1 , 0
       0      .1       0  298.55    .045       0   330.3      .1       0
  398.86      .1       0  895.78      .1       0
Bank Sta=298.55,330.3
XS Rating Curve= 0 ,0
Exp/Cntr(USF)=0,0
Exp/Cntr=0.3,0.1

Type RM Length L Ch R = 1 ,8366    ,320.9,307.6,287.2
XS GIS Cut Line= 4
2179341.25442241298866.2892952252178845.10640207298939.893671868
2178498.89322305299046.2111047972178215.38006857299509.646068844
#Sta/Elev= 30
       0 2007.47    71.9 1995.01  125.141980.497   160.8 1974.46   181.3 1967.53
   273.7 1960.03   339.9 1957.13     367 1963.42  423.161964.325   442.1 1963.32
   473.8 1955.29  522.691953.988   537.4 1954.61   552.51951.064   575.2 1948.03
   588.9 1948.37   599.2 1951.58   688.4 1954.49   715.9 1952.76   796.7 1952.87
   865.9 1948.98   877.4 1950.82   932.21951.333   988.9 1952.34  1015.8 1949.98
    1162 1951.57  1219.7 1958.23  1259.81965.265  1346.6 1989.05    1407 2012.01
#Mann= 8 ,-1 , 0
       0     .06       0  125.14    .055       0  423.16     .05       0
  522.69      .1       0   552.5    .045       0   599.2      .1       0
   932.2      .1       0  1259.8      .1       0
#XS Ineff= 2 , 0
           527.9 1955.38
Permanent Ineff=
       F       F
Bank Sta=552.5,599.2
XS Rating Curve= 0 ,0
Exp/Cntr(USF)=0,0
Exp/Cntr=0.3,0.1

Type RM Length L Ch R = 1 ,8058    ,168.4,159.8,145.9
XS GIS Cut Line= 3
2178864.66019395298283.9497757692178460.79530153298916.671440554
2178151.16555068299522.468779178
#Sta/Elev= 30
       0 2070.17   33.59 2055.75   68.962037.167  134.992003.356   155.2 1995.68
   205.8 1987.79   217.5 1982.37   264.2 1978.23   283.7 1966.79   318.7 1953.07
   365.4 1950.75  430.981951.221   478.1 1952.17   509.4 1971.28   521.1 1974.39
   556.1 1975.12  576.661962.693  599.091948.758   614.5 1945.54   625.5 1946.24
     634 1949.41   645.7 1951.45   680.7 1949.37  967.921949.092  1063.9 1950.27
 1170.261948.354  1240.8 1949.74  1280.5 1957.61  1336.6 1977.22    1431  2020.3
#Mann= 10 ,-1 , 0
       0      .1       0   33.59     .06       0   68.96      .1       0
  134.99     .06       0  430.98    .055       0  576.66      .1       0
  599.09    .045       0     634      .1       0  967.92      .1       0
 1170.26      .1       0
#XS Ineff= 2 , 0
          546.01 1974.65  1107.8         1955.34
Permanent Ineff=
       F       F
Bank Sta=599.09,634
XS Rating Curve= 0 ,0
Exp/Cntr(USF)=0,0
Exp/Cntr=0.3,0.1

Type RM Length L Ch R = 1 ,7898    ,241.6,237,228.3
XS GIS Cut Line= 4
2178400.21556767298344.5295096312178373.29124151298684.449127415
2178403.58110844298970.5200928762178107.41352067299532.565401489
#Sta/Elev= 30
       0 2037.66   43.772024.521   122.8 1993.71   136.3 1990.72   159.4 1990.28
   175.8 1983.65     212 1987.09   231.8 1984.63   258.1 1986.52     291 1984.93
   307.5 1992.83  313.261993.548     341  1989.6   366.8  1979.8     380  1972.4
   399.7  1950.8   406.3 1947.17  415.21 1946.03   426.1 1943.01  451.441946.032
   462.4  1949.6     502 1950.18   525.1 1947.75   683.3 1949.55  788.531948.212
  996.821947.985  1068.5 1948.47  1098.2 1955.62  1142.7 1972.54    1264 2030.82
#Mann= 7 ,-1 , 0
       0      .1       0   43.77     .06       0  313.26      .1       0
  415.21    .045       0  451.44      .1       0  788.53      .1       0
  996.82      .1       0
#XS Ineff= 2 , 0
                          900.17         1955.07
Permanent Ineff=
       F       F
Bank Sta=415.21,451.44
XS Rating Curve= 0 ,0
Exp/Cntr(USF)=0,0
Exp/Cntr=0.3,0.1

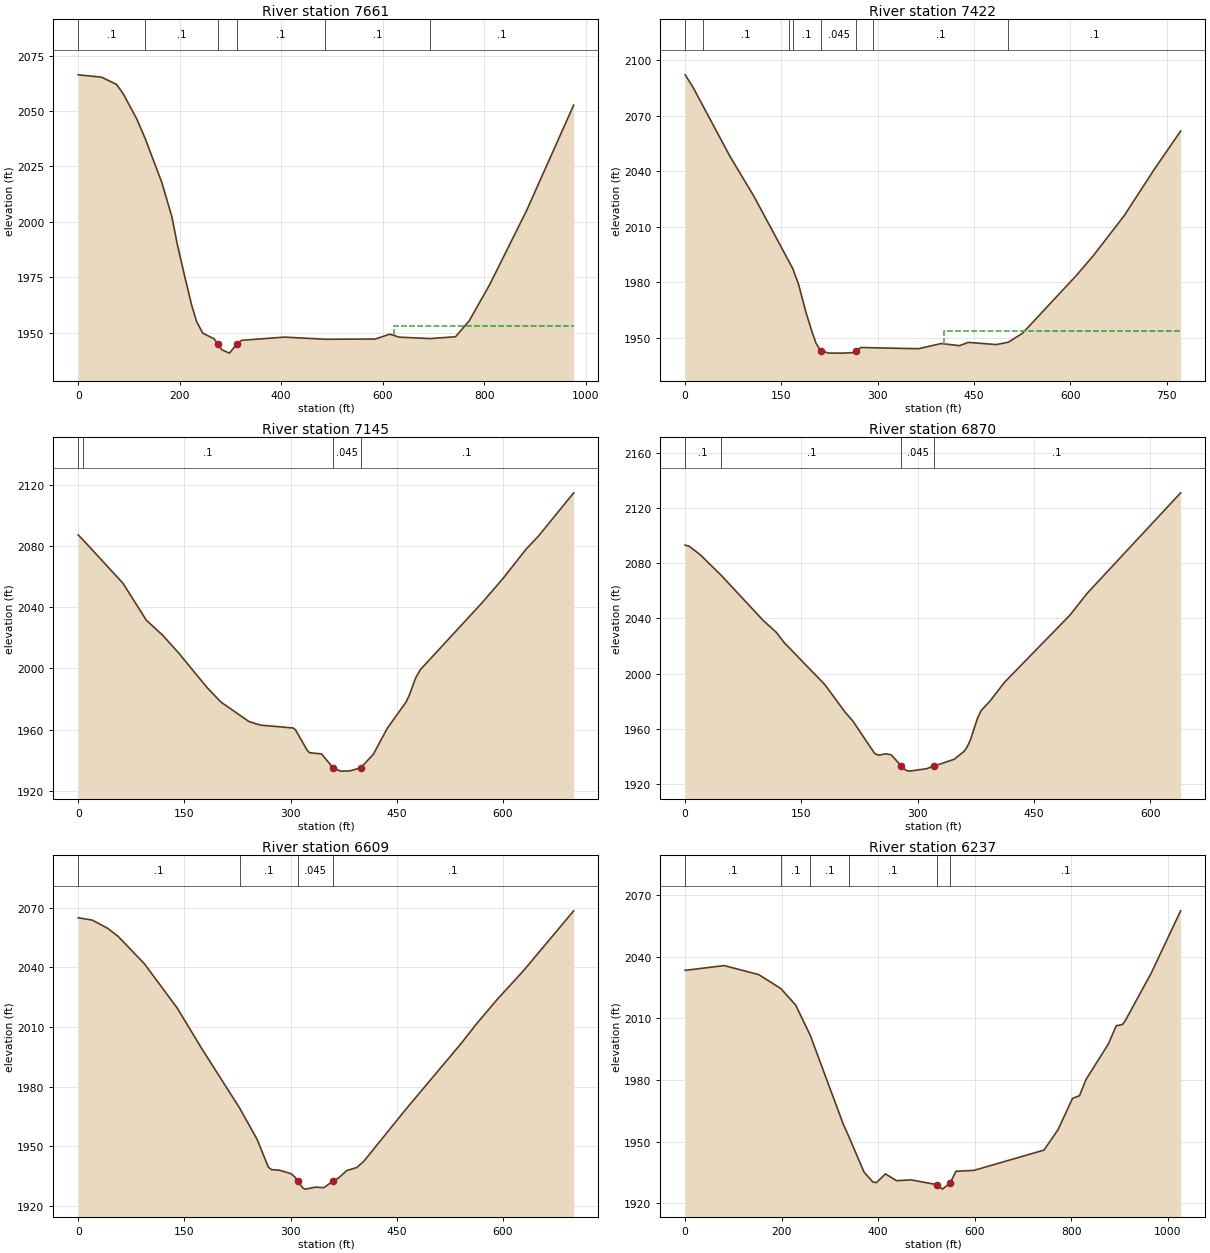
Type RM Length L Ch R = 1 ,7661    ,239,238.9,238.7
XS GIS Cut Line= 4
2178157.89663222298667.6214235642178178.08987684298856.091706692
2178292.51826302299047.9275305892178063.66149065 299562.85526842
#Sta/Elev= 30
       0 2066.38      46 2065.33    75.7 2062.04    88.9 2057.75   115.3 2046.52
  132.262037.485   164.8 2017.77   184.7 2002.25   195.3 1989.87   210.5 1974.78
   223.9 1962.12   233.5 1954.89   245.5 1949.74   267.8 1947.18  275.051944.964
   283.1  1942.2   298.1 1940.72  312.921944.966     322  1946.5   406.5 1947.95
  486.98 1946.99   585.3 1947.08   614.1 1949.28   632.7 1947.93  693.761947.297
   743.6 1948.12   770.9 1955.43   810.7 1971.59   883.3 2004.93   976.4 2052.71
#Mann= 6 ,-1 , 0
       0      .1       0  132.26      .1       0  275.05    .045       0
  312.92      .1       0  486.98      .1       0  693.76      .1       0
#XS Ineff= 2 , 0
                          622.18         1952.79
Permanent Ineff=
       F       F
Bank Sta=275.05,312.92
XS Rating Curve= 0 ,0
Exp/Cntr(USF)=0,0
Exp/Cntr=0.3,0.1

Type RM Length L Ch R = 1 ,7422    ,262.6,277.8,279.5
XS GIS Cut Line= 3
2177908.84661523298879.6504920832178130.97230606299226.301191407
 2178046.8337868299576.317431501
#Sta/Elev= 30
       0 2092.01    11.8 2085.57    27.3 2075.52    69.5 2048.12   107.5 2026.11
  161.791991.044  167.771987.115   176.6 1978.81   188.3 1963.45   197.7    1953
   203.8 1946.88  210.981942.956   223.3 1941.59   245.2 1941.56   262.3 1941.85
  266.771942.959   273.7 1944.62  292.971944.445   363.6 1943.95   398.7 1946.75
   427.4  1945.6   440.9 1947.37   484.8 1946.19  503.231947.458   525.3 1952.26
   609.6 1983.65   636.6 1994.64   683.9 2015.93     731 2041.11   771.7 2061.62
#Mann= 8 ,-1 , 0
       0      .1       0    27.3      .1       0  161.79      .1       0
  167.77      .1       0  210.98    .045       0  266.77      .1       0
  292.97      .1       0  503.23      .1       0
#XS Ineff= 2 , 0
                          402.77         1953.52
Permanent Ineff=
       F       F
Bank Sta=210.98,266.77
XS Rating Curve= 0 ,0
Exp/Cntr(USF)=0,0
Exp/Cntr=0.3,0.1

Type RM Length L Ch R = 1 ,7145    ,264.6,274.7,285.7
XS GIS Cut Line= 3
2177871.82566676298893.1126551632177902.11553369299206.107946786
2177838.17025906299586.414053811
#Sta/Elev= 30
       0 2087.21    6.392084.188    63.3  2055.6    96.3 2031.47   119.4 2021.62
   142.3 2009.87   182.4 1987.33   201.8 1977.95   241.3 1965.26   257.8 1962.92
   303.9 1961.04   307.2 1959.72   323.8 1946.31   327.1 1944.89   343.8 1944.13
  360.291934.998   370.4 1932.88   383.7 1933.01     3991934.998     417 1943.84
   436.9 1960.99   463.5 1978.17   467.8 1982.43   476.8 1993.72   483.5  1999.2
     570 2042.53   599.9 2058.54   633.2 2078.05     650 2086.24   700.1 2114.68
#Mann= 4 ,-1 , 0
       0      .1       0    6.39      .1       0  360.29    .045       0
     399      .1       0
Bank Sta=360.29,399
XS Rating Curve= 0 ,0
Exp/Cntr(USF)=0,0
Exp/Cntr=0.3,0.1

Type RM Length L Ch R = 1 ,6870    ,258.7,260.8,261
XS GIS Cut Line= 3
 2177844.9013406298856.0917066922177723.74187287 299064.75523444
2177457.86415203299360.922822212
#Sta/Elev= 30
       0 2093.01       5 2092.28    19.4 2086.09   46.522071.175   100.5 2038.57
   117.8 2029.76   127.9 2022.37   180.2 1992.03   206.7 1971.83   216.2  1965.8
   244.5 1942.18   249.4 1940.91   259.2 1941.93   265.8 1941.19  279.141932.965
   284.9 1929.95   289.3 1929.37   311.4  1931.1  320.751932.966   347.1 1937.94
   359.9 1943.74   363.4 1946.41     368 1951.86   377.3 1967.88   381.9 1973.18
   393.6 1980.28   412.1 1993.74   496.5 2042.35     519 2058.31   639.3 2130.89
#Mann= 4 ,-1 , 0
       0      .1       0   46.52      .1       0  279.14    .045       0
  320.75      .1       0
Bank Sta=279.14,320.75
XS Rating Curve= 0 ,0
Exp/Cntr(USF)=0,0
Exp/Cntr=0.3,0.1

Type RM Length L Ch R = 1 ,6609    ,372.7,372.7,369.7
XS GIS Cut Line= 3
2177780.95606596298724.8356166562177592.48578284298849.360625151
2177242.46954274299169.086998314
#Sta/Elev= 30
       0    2065      20 2063.79    41.6  2059.7    56.6 2055.55    93.7 2041.75
   139.9 2019.51   175.6 1998.51  227.891969.256   252.9 1953.29   268.7 1939.37
   273.2 1938.13   284.4 1937.84   300.6 1936.12   306.4 1934.34  310.331932.272
   317.6 1928.86     321 1928.32   335.4 1929.31   347.1 1929.06  359.631932.271
     368 1933.98   379.6 1937.71   393.5 1939.17   403.7 1942.42   462.1 1968.18
   542.2  2002.2     562 2011.24   593.2 2024.37   628.1 2037.92     700 2068.48
#Mann= 4 ,-1 , 0
       0      .1       0  227.89      .1       0  310.33    .045       0
  359.63      .1       0
Bank Sta=310.33,359.63
XS Rating Curve= 0 ,0
Exp/Cntr(USF)=0,0
Exp/Cntr=0.3,0.1

Type RM Length L Ch R = 1 ,6237    ,470.6,471.4,467.5
XS GIS Cut Line= 3
2177632.87227208 298310.874101932177340.07022508298580.117363541
2176878.99113957299007.541041348
#Sta/Elev= 30
       0 2033.31    80.8 2035.62   152.4 2031.23  198.232024.456     229 2016.42
  259.092001.746     328 1958.24  338.711952.705   370.6 1935.18   389.2  1930.3
   396.5  1930.1   414.8 1934.34     438 1931.01   468.2  1931.4   521.6 1929.09
   533.2 1926.91  548.971929.888     561 1935.59   598.6 1936.04   743.4  1945.9
   772.3 1955.75   802.5 1971.04     817 1972.35   830.2 1980.12   876.8 1997.51
     893 2006.34   906.4 2007.03   912.3 2009.04   965.4  2031.9  1026.5 2062.25
#Mann= 6 ,-1 , 0
       0      .1       0  198.23      .1       0  259.09      .1       0
  338.71      .1       0   521.6    .045       0  548.97      .1       0
Bank Sta=521.6,548.97
XS Rating Curve= 0 ,0
Exp/Cntr(USF)=0,0
Exp/Cntr=0.3,0.1

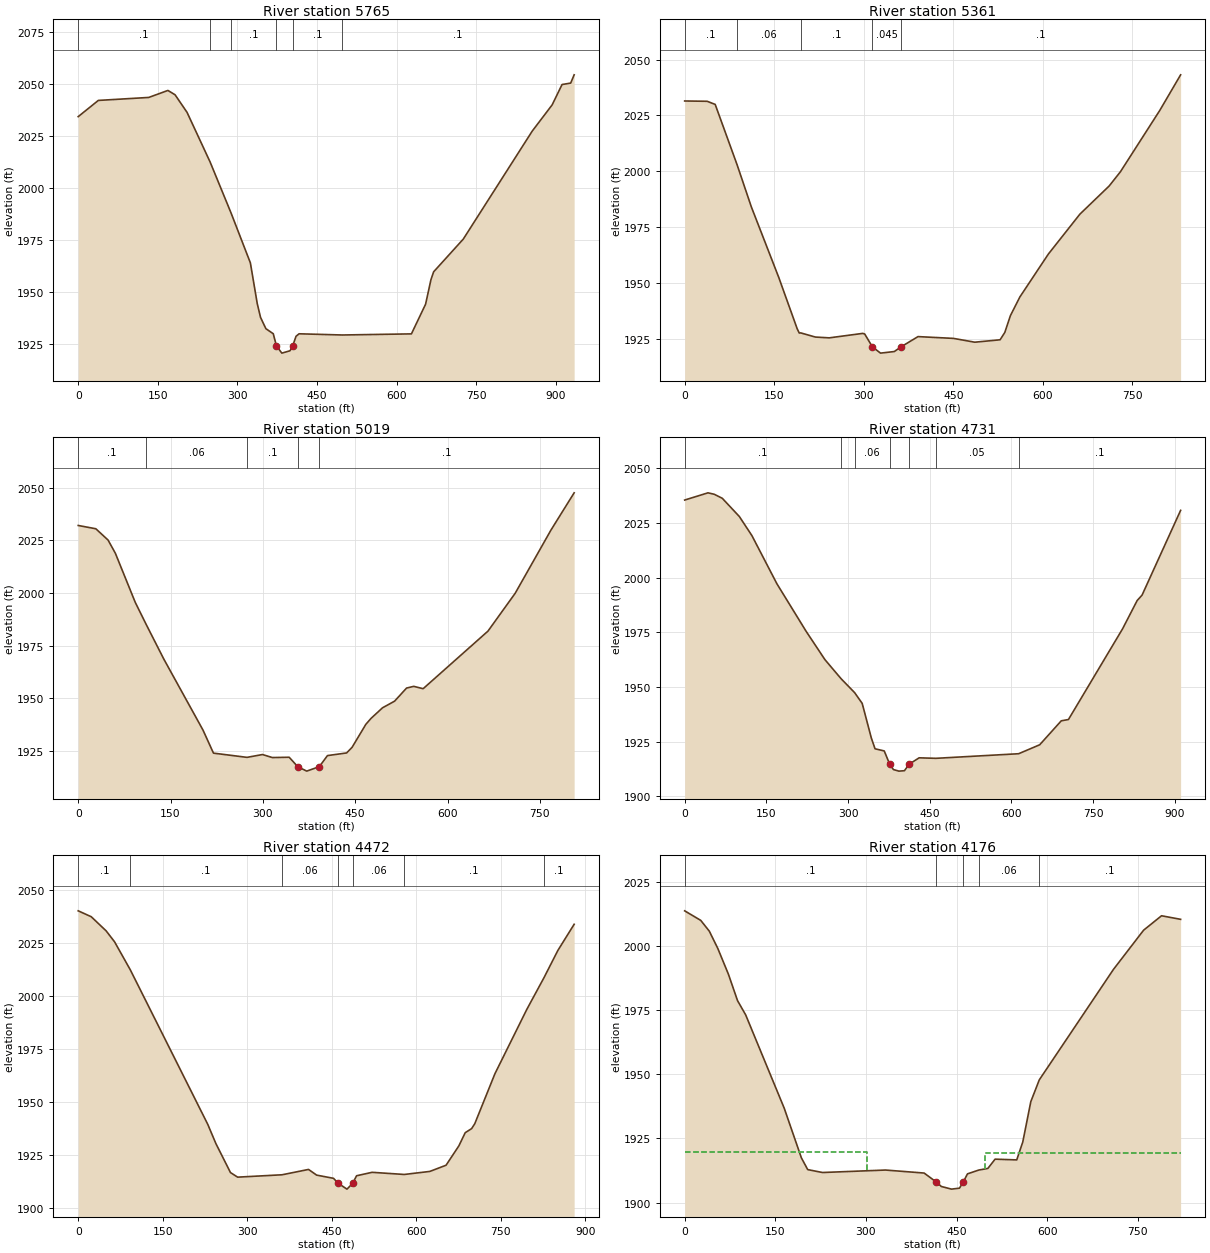
Type RM Length L Ch R = 1 ,5765    ,412.2,403.8,380.6
XS GIS Cut Line= 3
2177306.41481738298021.437595698 2176942.9364142298364.722754252
2176660.23098951298694.545749725
#Sta/Elev= 30
       0 2034.41    37.9 2042.22   132.9 2043.66     169 2047.03   182.5 2044.94
   205.1 2036.45  248.542012.528  288.111987.884   324.4 1963.91   337.3 1944.33
   343.5 1937.66   353.6  1932.2   367.5 1929.77  373.581923.807   383.7 1920.42
   399.1 1921.56  403.941923.805   410.4 1928.54   416.2 1929.74  497.51 1929.16
   627.8  1929.7   654.5    1944   664.6 1955.83   669.6 1959.59   725.5 1975.38
   855.4 2027.43     893  2040.1   911.6 2049.88   927.9 2050.58   934.4 2054.56
#Mann= 6 ,-1 , 0
       0      .1       0  248.54      .1       0  288.11      .1       0
  373.58    .045       0  403.94      .1       0  497.51      .1       0
Bank Sta=373.58,403.94
XS Rating Curve= 0 ,0
Exp/Cntr(USF)=0,0
Exp/Cntr=0.3,0.1

Type RM Length L Ch R = 1 ,5361    ,332.4,342.3,345.4
XS GIS Cut Line= 4
2176778.02491646297745.463252547 2176717.4451826297947.395698755
2176690.52085644298166.1558488142176465.02962484298495.978844287
#Sta/Elev= 30
       0 2031.47    37.7 2031.33    51.1 2029.94   87.882002.886   111.7 1984.08
   157.6 1952.54   188.4 1929.62   191.9 1927.68  194.61  1927.7     219 1925.86
   242.1  1925.5   298.3  1927.5   301.6 1927.22  314.391921.495   328.1 1918.67
   351.2 1919.38  362.541921.497   390.9 1926.06   450.3 1925.26     486 1923.56
   528.4 1924.64   536.3 1927.93   545.6  1935.4   561.5 1943.79   609.2 1962.97
   662.1 1980.85     711 1993.41   729.9 1999.78     796 2027.29   830.8 2043.17
#Mann= 5 ,-1 , 0
       0      .1       0   87.88     .06       0  194.61      .1       0
  314.39    .045       0  362.54      .1       0
Bank Sta=314.39,362.54
XS Rating Curve= 0 ,0
Exp/Cntr(USF)=0,0
Exp/Cntr=0.3,0.1

Type RM Length L Ch R = 1 ,5019    ,289.7,287.6,278.2
XS GIS Cut Line= 4
2176599.65125565297725.2700079262176421.27759483297984.416647227
2176290.02150479298189.7146342052176226.07623016298428.668028884
#Sta/Elev= 30
       0 2032.11    28.6 2030.55    48.5 2025.17    60.4 2018.86    92.7 1995.51
  110.381985.049     139 1968.58   202.7 1934.78   219.7 1923.81  274.16  1921.8
   299.4 1923.14   315.3 1921.71   342.7 1921.85  356.611917.376   371.2 1915.25
  391.611917.377   404.9 1922.64     436  1923.9   444.9 1926.59   467.2  1937.5
   475.7 1940.35   494.4 1945.39   513.9 1948.53   533.4 1954.77   545.1 1955.58
   560.3 1954.46   665.6 1981.85   709.8 1999.85   767.9 2029.91   805.6 2047.64
#Mann= 5 ,-1 , 0
       0      .1       0  110.38     .06       0  274.16      .1       0
  356.61    .045       0  391.61      .1       0
Bank Sta=356.61,391.61
XS Rating Curve= 0 ,0
Exp/Cntr(USF)=0,0
Exp/Cntr=0.3,0.1

Type RM Length L Ch R = 1 ,4731    ,257.3,258.9,258.4
XS GIS Cut Line= 4
2176306.84920865297597.3794586612176155.39987399297846.429475651
2176084.72351782298142.5970634232176118.37892552298455.592355045
#Sta/Elev= 30
       0 2035.53    42.8 2038.84    54.3 2038.18    69.1 2036.33   100.4    2028
   123.5 2019.25   169.5 1997.16   223.3 1975.35   257.7 1962.45   287.31953.741
  312.171947.369     326 1942.47   342.8 1926.62   349.6 1921.69   366.5  1920.7
  376.471914.665   383.4 1912.17   393.5 1911.46   403.6 1911.65  412.371914.665
   430.6 1917.55  461.521917.321  613.291919.422     652 1923.52   691.6 1934.48
   704.8 1935.08   804.2 1976.59     831 1989.54     840 1992.02   910.8 2030.81
#Mann= 7 ,-1 , 0
       0      .1       0   287.3      .1       0  312.17     .06       0
  376.47    .045       0  412.37     .06       0  461.52     .05       0
  613.29      .1       0
Bank Sta=376.47,412.37
XS Rating Curve= 0 ,0
Exp/Cntr(USF)=0,0
Exp/Cntr=0.3,0.1

Type RM Length L Ch R = 1 ,4472    ,295.5,296.8,296.8
XS GIS Cut Line= 4
 2176098.1856809297466.123368626  2175906.349857 297809.40852718
2175862.59782699297964.2234026062175674.12754386298230.101123446
#Sta/Elev= 30
       0 2039.97    23.1 2037.19    49.5 2030.53    64.5 2025.36   92.552012.083
   229.9 1939.25   244.3 1930.18   270.2 1916.51   282.9 1914.35  361.741915.465
   408.7 1917.99   423.1  1915.3     453  1913.8  461.581911.403   476.9  1908.7
  486.991911.404   493.9    1915   521.5 1916.63  578.611915.619   623.9 1917.05
   652.7 1919.97   675.4 1929.09   686.7 1935.31   698.1 1937.25   703.7 1939.57
   739.4 1963.12   795.8 1993.37  826.312008.356   851.2 2021.33     880 2033.62
#Mann= 7 ,-1 , 0
       0      .1       0   92.55      .1       0  361.74     .06       0
  461.58    .045       0  486.99     .06       0  578.61      .1       0
  826.31      .1       0
Bank Sta=461.58,486.99
XS Rating Curve= 0 ,0
Exp/Cntr(USF)=0,0
Exp/Cntr=0.3,0.1

Type RM Length L Ch R = 1 ,4176    ,298.6,285.8,247.9
XS GIS Cut Line= 4
2175849.13566391297291.1152485792175707.78295156297637.765947903
2175627.00997308297779.1186602482175576.52686153 298058.45854417
#Sta/Elev= 30
       0 2013.66    26.6 2009.94    40.8 2005.73    54.9 1998.98    72.4 1988.98
    87.5 1978.69     101 1973.13   164.8 1936.79   193.2 1917.46   203.7 1912.88
   228.2 1911.75   332.5 1912.71   396.4 1911.54  416.731908.011   424.9 1906.31
   441.7 1905.28   454.9 1905.65  461.051908.014   468.2 1911.23  486.881912.706
   501.9 1913.34   513.9 1916.95   549.7 1916.66   559.7 1923.63     573 1939.34
  587.031947.827   709.7 1990.81   759.7 2006.11   789.4 2011.74     821 2010.35
#Mann= 5 ,-1 , 0
       0      .1       0  416.73    .045       0  461.05      .1       0
  486.88     .06       0  587.03      .1       0
#XS Ineff= 2 , 0
          302.43 1919.73   497.4         1919.18
Permanent Ineff=
       F       F
Bank Sta=416.73,461.05
XS Rating Curve= 0 ,0
Exp/Cntr(USF)=0,0
Exp/Cntr=0.3,0.1

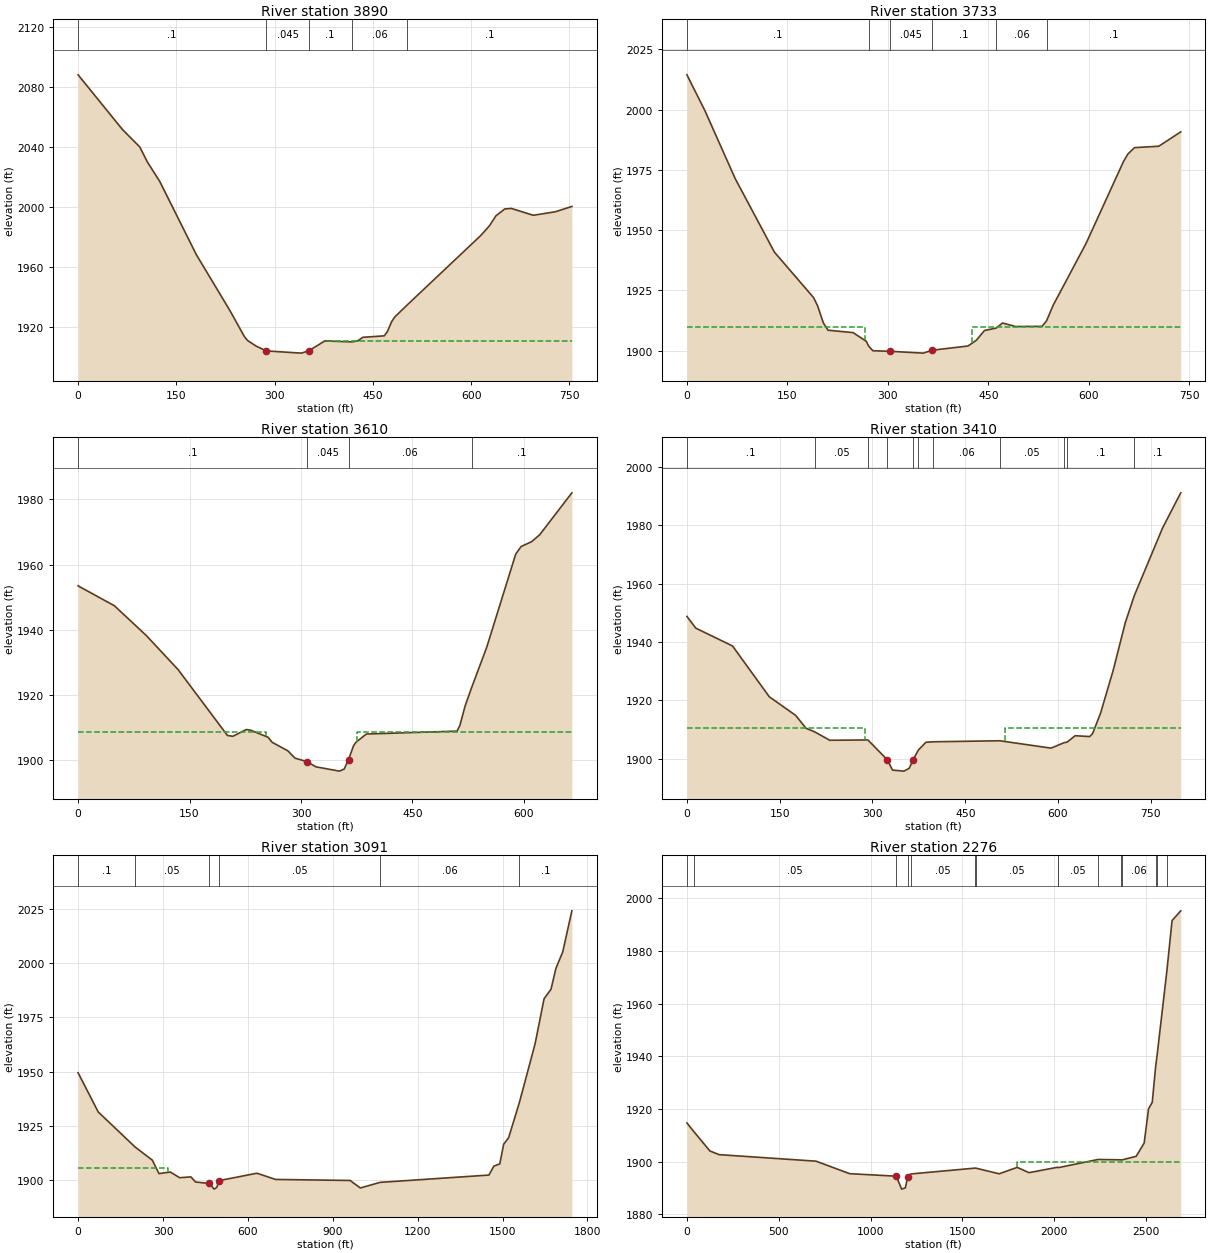
Type RM Length L Ch R = 1 ,3890    ,157.3,157.3,157.3
XS GIS Cut Line= 3
2175327.47684454297402.1780939932175573.16132076 297812.77406795
2175515.94712766298082.017329561
#Sta/Elev= 30
       0 2087.96    67.5 2051.71    94.2 2039.97   105.7 2030.05   124.8 2016.96
   180.3 1968.55   231.9 1931.12   253.9 1913.89   258.6 1911.38   271.2 1907.75
  287.251904.422   340.6 1902.95  351.931904.424   376.5 1911.06  417.741910.411
   426.9 1911.08   434.5 1913.45   467.4 1914.45   472.2 1917.36   478.5 1923.84
   483.5 1927.02  502.19 1934.91   614.3 1981.01   627.7 1987.49   637.8 1994.23
   651.2 1998.79   661.3 1999.15   694.8 1994.59   728.4 1996.91   753.7 2000.46
#Mann= 5 ,-1 , 0
       0      .1       0  287.25    .045       0  351.93      .1       0
  417.74     .06       0  502.19      .1       0
#XS Ineff= 2 , 0
                          380.31         1911.31
Permanent Ineff=
       F       F
Bank Sta=287.25,351.93
XS Rating Curve= 0 ,0
Exp/Cntr(USF)=0,0
Exp/Cntr=0.3,0.1

Type RM Length L Ch R = 1 ,3733    ,123,123,123
XS GIS Cut Line= 4
2175107.46585053297614.333293731 2175263.6094391  297780.1352486
2175490.58104722297765.6476991462175506.67832439298047.350049652
#Sta/Elev= 30
       0 2014.39      27 1999.41      72 1971.36   130.6 1940.83   189.2 1921.92
   195.2 1918.45   203.7 1911.45   210.7 1908.42   248.1 1907.43   267.9  1903.8
   271.2 1901.86   277.7 1899.91   303.8 1899.67   352.9 1898.92   366.1 1900.13
   419.7 1901.88   432.2 1904.28   444.2  1908.3  461.88 1909.32   471.2 1911.42
   490.9 1909.96   530.3 1910.03     5371912.336   546.8 1918.77     596 1944.47
   651.9 1978.46   658.5 1981.56   668.3 1984.18   704.5 1984.76   737.3 1990.71
#Mann= 6 ,-1 , 0
       0      .1       0   271.2     .05       0   303.8    .045       0
   366.1      .1       0  461.88     .06       0     537      .1       0
#XS Ineff= 2 , 0
          265.51  1909.7  425.65          1909.7
Permanent Ineff=
       F       F
Bank Sta=303.8,366.1
XS Rating Curve= 0 ,0
Exp/Cntr(USF)=0,0
Exp/Cntr=0.3,0.1

Type RM Length L Ch R = 1 ,3610    ,163.9,199.3,212
XS GIS Cut Line= 4
2174986.73627175297699.648862741  2175207.268969297839.695174136
2175410.09466136297847.7438127222175490.58104722 298031.25277248
#Sta/Elev= 30
       0 1953.44    48.9 1947.32    91.7 1938.19   134.4 1927.74     201 1907.44
   208.2 1907.18   226.3 1909.26   232.4 1909.05   255.7 1906.88   261.2 1905.33
   282.2 1902.73     292 1900.46   307.6 1899.42   320.2 1897.79   351.8 1896.47
   358.1  1897.1  363.971900.007   370.7 1904.24   373.9 1905.34     388 1907.88
     510 1908.77   513.8 1910.49     521 1916.58  529.581922.112   549.9  1934.5
     589 1963.19   596.2 1965.53   610.5 1967.04   621.3 1969.16   664.6 1982.05
#Mann= 4 ,-1 , 0
       0      .1       0   307.6    .045       0  363.97     .06       0
  529.58      .1       0
#XS Ineff= 2 , 0
          252.34  1908.5  374.87          1908.5
Permanent Ineff=
       F       F
Bank Sta=307.6,363.97
XS Rating Curve= 0 ,0
Exp/Cntr(USF)=0,0
Exp/Cntr=0.3,0.1

Type RM Length L Ch R = 1 ,3410    ,312.6,319.5,329.7
XS GIS Cut Line= 4
2174922.34716306297678.7224024182175078.49075163297868.670273045
2175176.68414237298028.0333170462175385.94874561298327.442672442
#Sta/Elev= 30
       0 1948.78    14.3 1944.77    73.7 1938.64   133.2 1921.21   175.7 1914.84
   192.6 1910.41  206.621909.167   230.9 1906.29  292.581906.395  324.13 1899.57
   332.4 1896.05     351  1895.7   359.4 1896.68   365.61899.567  374.381902.997
   386.4  1905.6  398.35 1905.77  506.021906.117   588.7 1903.59  610.26  1905.5
  614.611905.641   627.7 1907.85   651.2 1907.56   655.9 1908.59   668.8 1915.61
   689.1 1930.21   708.8 1946.66  723.19 1955.85     769 1979.12   798.4  1991.2
#Mann= 11 ,-1 , 0
       0      .1       0  206.62     .05       0  292.58      .1       0
  324.13    .045       0   365.6      .1       0  374.38     .05       0
  398.35     .06       0  506.02     .05       0  610.26     .06       0
  614.61      .1       0  723.19      .1       0
#XS Ineff= 2 , 0
          287.69 1910.41  513.69         1910.41
Permanent Ineff=
       F       F
Bank Sta=324.13,365.6
XS Rating Curve= 0 ,0
Exp/Cntr(USF)=0,0
Exp/Cntr=0.3,0.1

Type RM Length L Ch R = 1 ,3091    ,826.3,815,793.9
XS GIS Cut Line= 4
2174769.43480663297594.4792491752174828.31830794297960.047653168
2174877.38789237 298615.126605292175553.57215066298855.887295363
#Sta/Elev= 30
       0 1949.43    71.2 1931.36  201.591915.218   262.3 1909.17   285.9 1902.97
   325.8 1903.71     359 1901.08   398.6 1901.48   415.1 1899.11  463.671898.443
   480.9 1895.83   490.2 1896.64   497.3 1899.71   631.9 1903.16     698 1900.29
   961.2 1899.82   997.4 1896.36 1067.181898.939  1451.8 1902.31  1469.2 1906.41
  1490.1 1907.45    1504 1916.53  1521.5 1919.49 1559.491935.719    1615 1962.77
  1646.8 1983.54  1671.2 1987.87  1688.6 1997.51  1712.6 2005.05    1745 2024.01
#Mann= 6 ,-1 , 0
       0      .1       0  201.59     .05       0  463.67    .045       0
   497.3     .05       0 1067.18     .06       0 1559.49      .1       0
#XS Ineff= 2 , 0
          318.82 1905.57
Permanent Ineff=
       F       F
Bank Sta=463.67,497.3
XS Rating Curve= 0 ,0
Exp/Cntr(USF)=0,0
Exp/Cntr=0.3,0.1

Type RM Length L Ch R = 1 ,2276    ,276.9,287.2,293.3
XS GIS Cut Line= 4
2174261.62855306297213.5471515662174046.23394378298186.188434136
2174480.38870312298643.9019788752175513.60971956298889.586455095
#Sta/Elev= 30
       0 1914.72    38.61911.371   125.3 1904.08   175.2  1902.7   702.8 1900.22
     886 1895.48    1140 1894.52  1169.1 1889.61  1189.2 1890.08  1202.4 1894.35
 1219.071895.365  1571.41897.602 1571.861897.599  1700.4 1895.43  1798.6 1897.87
  1862.9 1895.86 2018.421897.916 2023.251897.771 2238.891900.869 2362.371900.736
 2369.321900.696  2446.3 1902.06  2490.1  1907.1  2513.8  1920.1    2534 1922.56
  2552.61936.165 2561.64 1941.15 2613.19 1972.13  2641.9 1991.54  2689.1 1995.26
#Mann= 15 ,-1 , 0
       0     .12       0    38.6     .05       0    1140    .045       0
  1202.4     .06       0 1219.07     .05       0  1571.4      .1       0
 1571.86     .05       0 2018.42      .1       0 2023.25     .05       0
 2238.89     .06       0 2362.37     .05       0 2369.32     .06       0
  2552.6    .055       0 2561.64      .1       0 2613.19      .1       0
#XS Ineff= 2 , 0
                          1797.4         1899.73
Permanent Ineff=
       F       F
Bank Sta=1140,1202.4
XS Rating Curve= 0 ,0
Exp/Cntr(USF)=0,0
Exp/Cntr=0.3,0.1