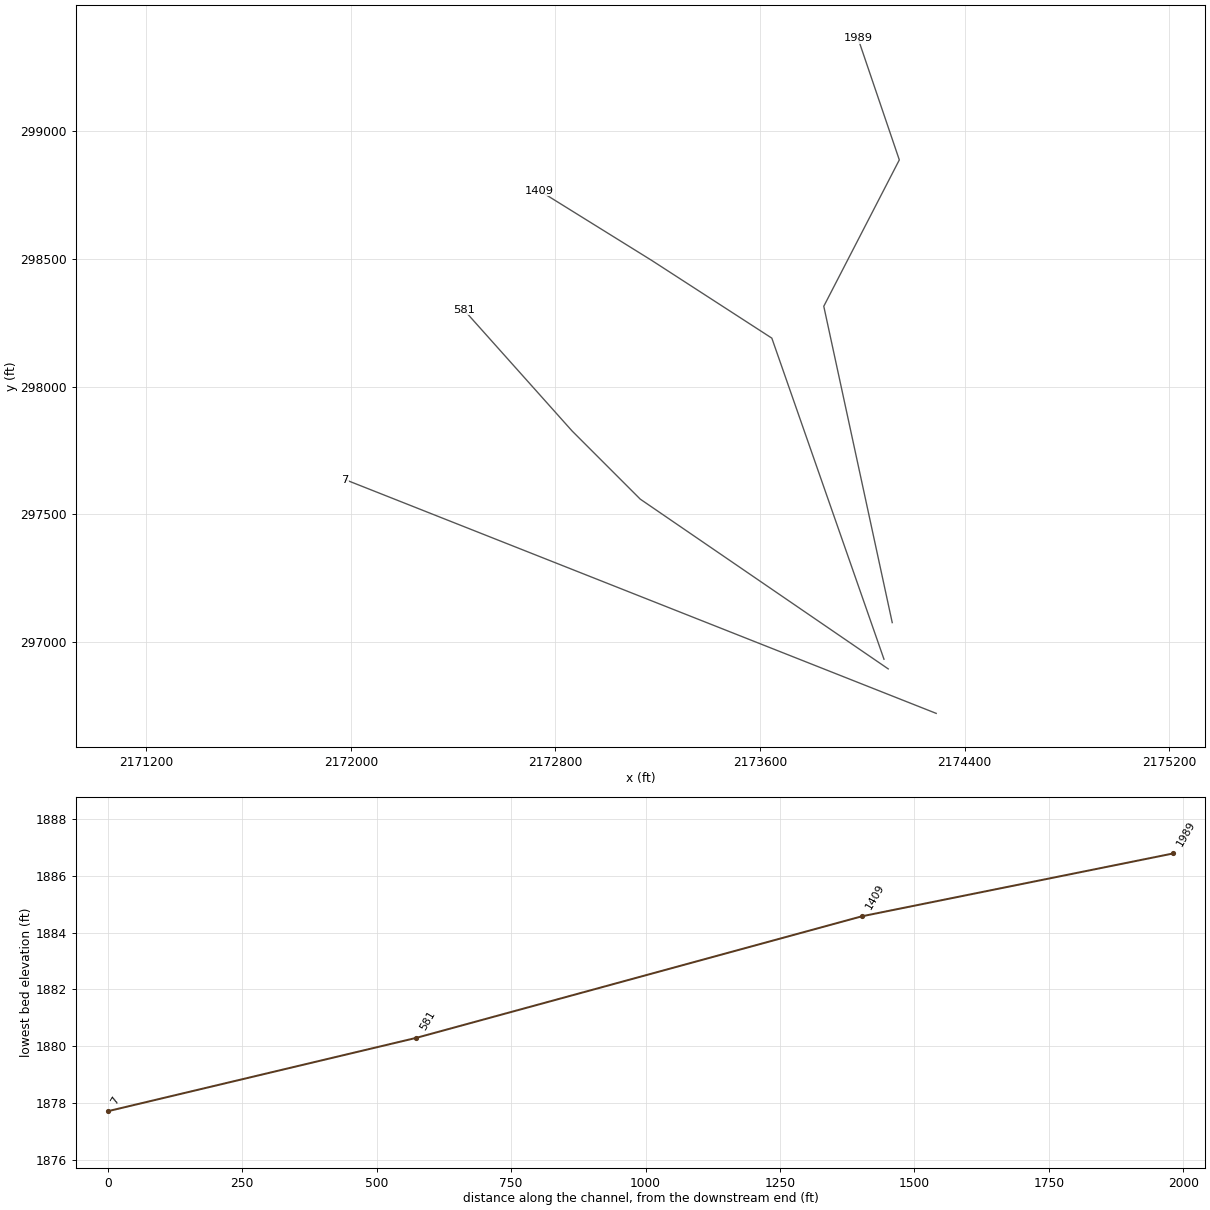
HEC-RAS study HOWARDCK.prj: HOWARDCK

--- HOWARDCK.g01 (geometry) --- (continued)

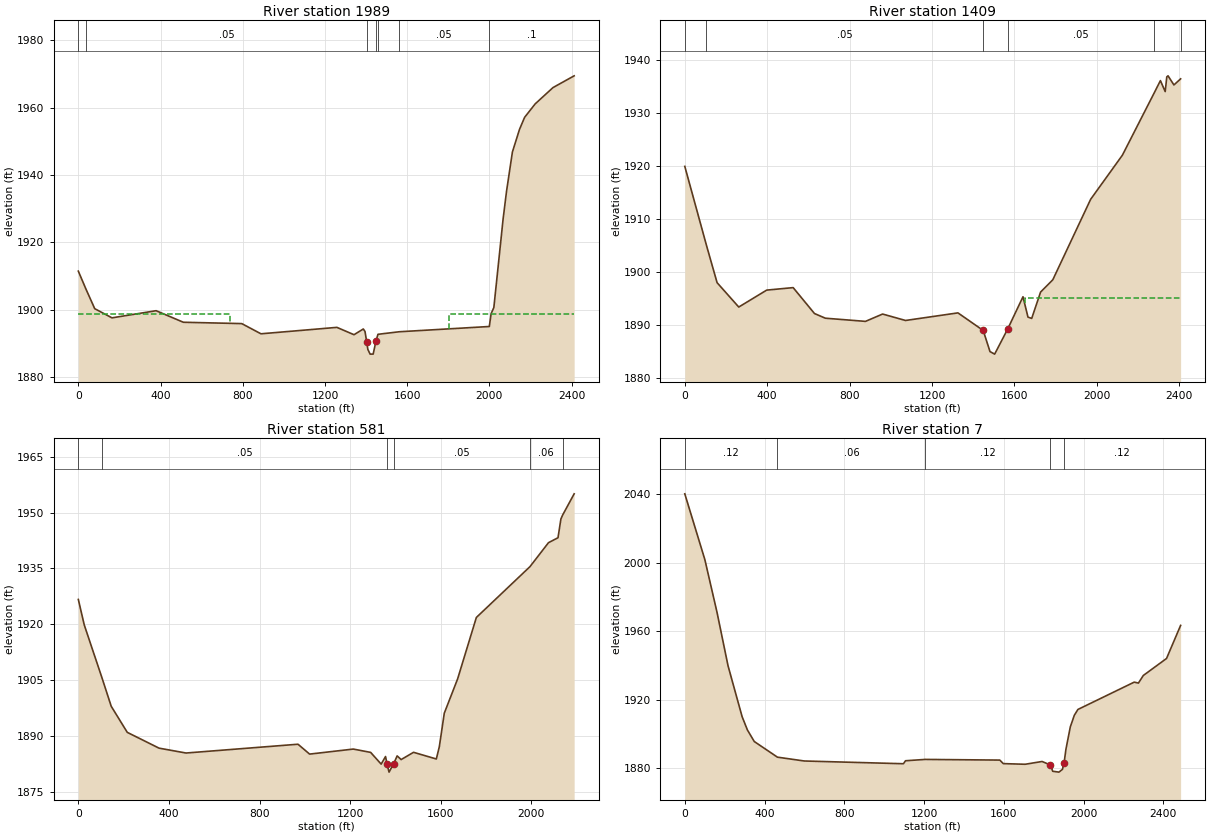
Type RM Length L Ch R = 1 ,1989    ,514.2,579.4,623.3
XS GIS Cut Line= 4
2174117.12266603  297076.9542095 2173849.3567337298314.217483021
2174144.82259007298886.6825797252173983.23969987 299362.19794231
#Sta/Elev= 30
       0 1911.43   37.051906.113    79.8 1900.28   163.7 1897.56   378.4 1899.68
   510.9 1896.25   795.1 1895.85   888.6 1892.82    1258 1894.73  1341.2 1892.55
  1386.5 1894.25  1394.8 1893.51 1403.061890.377  1408.6 1888.17  1419.7 1886.78
  1434.5 1886.79  1448.4 1890.74 1457.811892.668 1560.611893.422 1999.571894.989
  2008.3  1898.8  2021.6 1900.63  2066.6 1926.92  2083.3 1935.16  2111.9 1946.84
  2146.3 1953.54  2171.2 1957.13  2222.6 1961.13  2309.2 1965.97  2412.3 1969.47
#Mann= 7 ,-1 , 0
       0      .1       0   37.05     .05       0 1403.06    .045       0
  1448.4    .055       0 1457.81     .06       0 1560.61     .05       0
 1999.57      .1       0
#XS Ineff= 2 , 0
          740.26 1898.72  1803.9         1898.72
Permanent Ineff=
       F       F
Bank Sta=1403.06,1448.4
XS Rating Curve= 0 ,0
Exp/Cntr(USF)=0,0
Exp/Cntr=0.3,0.1

Type RM Length L Ch R = 1 ,1409    ,821,828.2,792.4
XS GIS Cut Line= 4
2174084.80608799296933.8379353242173646.22395745298189.567824868
2173175.32524887298494.2669892432172736.74311834298766.649575578
#Sta/Elev= 30
       0 1919.94  105.241905.061   156.8 1898.03     262 1893.44   397.6 1896.63
   526.1  1897.1   629.6 1892.22   682.3 1891.34   877.1 1890.74   960.4 1892.12
  1071.7 1890.91  1326.2 1892.34  1448.8 1889.03  1481.8 1885.05  1504.4 1884.57
  1567.8 1889.31    1642 1895.38  1666.2 1891.54  1684.3  1891.3  1727.4 1896.26
  1786.8 1898.58  1970.5 1913.74  2124.6 1922.05  2276.81933.612  2309.2  1936.1
  2332.4 1934.03  2340.1  1936.8  2346.2    1937  2374.8 1935.28  2407.3 1936.43
#Mann= 6 ,-1 , 0
       0      .1       0  105.24     .05       0  1448.8    .045       0
  1567.8     .05       0  2276.8    .055       0  2407.3     .05       0
#XS Ineff= 2 , 0
                         1649.69         1895.23
Permanent Ineff=
       F       F
Bank Sta=1448.8,1567.8
XS Rating Curve= 0 ,0
Exp/Cntr(USF)=0,0
Exp/Cntr=0.5,0.3

Type RM Length L Ch R = 1 ,581     ,545.6,574.1,586.4
XS GIS Cut Line= 4
2174101.47733857296895.9199437732173131.42587224297560.037338253
2172865.44580607297826.0174044242172441.14427194  298300.9818083
#Sta/Elev= 30
       0 1926.66    26.2 1919.81  104.241905.649   145.2 1897.98     216 1890.98
   356.2 1886.74   475.4 1885.43   969.6 1887.79  1020.9 1885.14  1213.7 1886.49
  1290.3  1885.6  1336.7 1882.45  1356.1 1884.49  1362.2 1882.58  1371.5  1880.3
  1392.4 1882.61  1407.2 1884.66  1424.9 1883.67  1479.7 1885.62  1580.2 1883.83
  1593.4 1887.11  1615.4 1896.13  1674.1 1905.31  1756.9 1921.82 1993.561935.471
  2075.3  1941.9  2117.3 1943.23  2130.1 1948.26 2137.611949.305  2188.6 1955.02
#Mann= 6 ,-1 , 0
       0      .1       0  104.24     .05       0  1362.2    .045       0
  1392.4     .05       0 1993.56     .06       0 2137.61     .05       0
Bank Sta=1362.2,1392.4
XS Rating Curve= 0 ,0
Exp/Cntr(USF)=0,0
Exp/Cntr=0.3,0.1

Type RM Length L Ch R = 1 ,7       ,7,7,7
XS GIS Cut Line= 2
     2174289.085      296721.981     2171976.815      297636.464
#Sta/Elev= 30
       0 2040.18   100.5 2001.82   161.4 1971.11   216.8 1939.82   287.5 1910.07
   313.9 1902.36   348.4 1895.59   464.5 1886.46   598.9 1884.22  1096.4 1882.62
    1107 1884.36  1205.8 1885.14  1579.7 1884.75  1597.2 1882.69  1706.8 1882.31
  1791.8 1883.93  1833.8 1881.87  1844.9 1878.23  1876.1 1877.72  1893.7 1879.31
  1901.9 1882.97  1911.4 1891.11  1933.4 1904.16  1953.4 1910.89  1971.4  1914.3
  2253.6 1930.24  2274.8 1929.71  2299.5 1934.14  2415.9 1944.07  2486.5 1963.37
#Mann= 5 ,-1 , 0
       0     .12       0   464.5     .06       0  1205.8     .12       0
  1833.8     .05       0  1901.9     .12       0
Bank Sta=1833.8,1901.9
XS Rating Curve= 0 ,0
Exp/Cntr(USF)=0,0
Exp/Cntr=0.3,0.1
Stream Node=ANGLINSCK       ,Main            , 0 , 0 ,Upstream end
Stream Node=ANGLINSCK       ,Main            , 0 , 1 ,Downstream end
Stream Node=GRBRRVTR1       ,Main            , 0 , 0 ,Upstream end
Stream Node=GRBRRVTR1       ,Main            , 0 , 1 ,Downstream end
Stream Node=GRBRRVTR2       ,Main            , 0 , 0 ,Upstream end
Stream Node=GRBRRVTR2       ,Main            , 0 , 1 ,Downstream end
Stream Node=GRBRRVTR4       ,Main            , 0 , 0 ,Upstream end
Stream Node=GRBRRVTR4       ,Main            , 0 , 1 ,Downstream end
Stream Node=HOMINYCK        ,Main            , 0 , 0 ,Upstream end
Stream Node=HOMINYCK        ,Main            , 0 , 1 ,Downstream end
Stream Node=HOWARDCK        ,Main            , 0 , 0 ,Upstream end
Stream Node=HOWARDCK        ,Main            , 0 , 1 ,Downstream end
Stream Node=JERCHODFT       ,Main            , 0 , 0 ,Upstream end
Stream Node=JERCHODFT       ,Main            , 0 , 1 ,Downstream end
Stream Node=JERCHODFTT1     ,Main            , 0 , 0 ,Upstream end
Stream Node=JERCHODFTT1     ,Main            , 0 , 1 ,Downstream end
Stream Node=LITTLECK2       ,Main            , 0 , 0 ,Upstream end
Stream Node=LITTLECK2       ,Main            , 0 , 1 ,Downstream end
Stream Node=SLPHRLCKRN      ,Main            , 0 , 0 ,Upstream end
Stream Node=SLPHRLCKRN      ,Main            , 0 , 1 ,Downstream end
Stream Node=SLSHLCKRN       ,Main            , 0 , 0 ,Upstream end
Stream Node=SLSHLCKRN       ,Main            , 0 , 1 ,Downstream end
Stream Node=YOUNGSCK        ,Main            , 0 , 0 ,Upstream end
Stream Node=YOUNGSCK        ,Main            , 0 , 1 ,Downstream end
LCMann Table=0

Chan Stop Cuts=-1
Use User Specified Reach Order=0
Composite Channel Slope=5